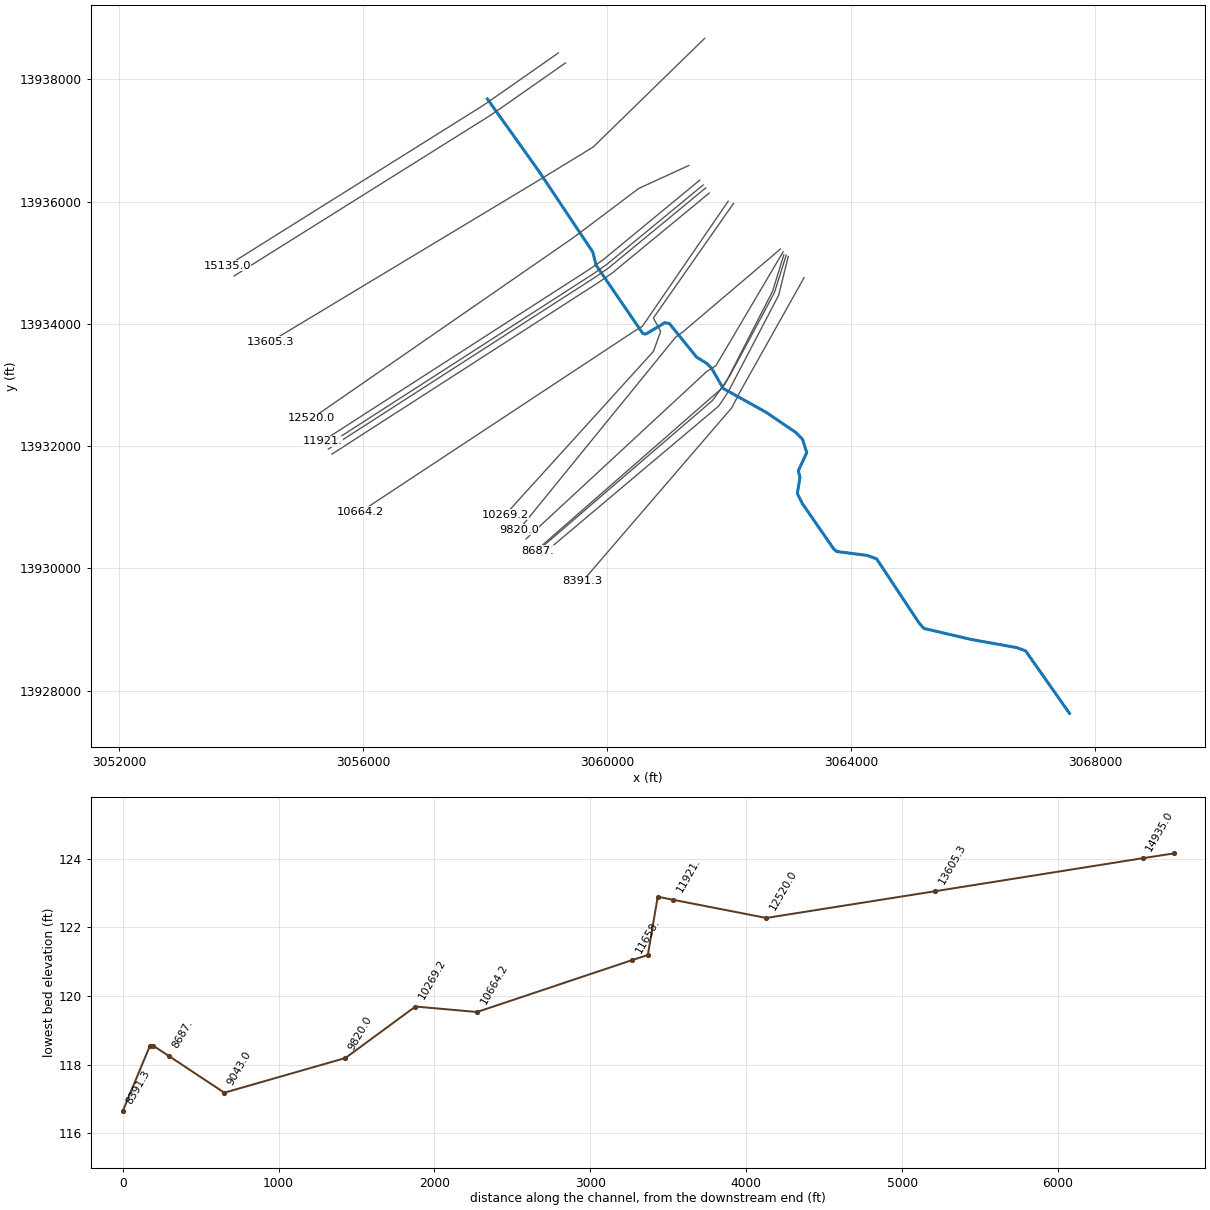
--- K133-00-00.prj (project) ---

Proj Title=K133-00-00
Current Plan=p02
Default Exp/Contr=.3,.1
English Units
Geom File=g01
Flow File=f01
Flow File=f02
Flow File=f04
Plan File=p01
Plan File=p02
Plan File=p04
Y Axis Title=Elevation
X Axis Title(PF)=Main Channel Distance
X Axis Title(XS)=Station
BEGIN DESCRIPTION:
Cypress Creek Watershed
Dry Gully
HCFCD Unit K133-00-00
Flood Hazard Model
10, 2, 1, 0.2%
Filename K133-00-00
Prepared by:  Halff Associates  DATE:  03/26/04
Reviewed by:  _____________________  DATE:  __________________
STATUS (Final)
END DESCRIPTION:
DSS Export Rating Curves= 0
DSS Export Rating Curve Sorted= 0
DSS Export Volume Flow Curves= 0
DXF OffsetX= 0
DXF OffsetY= 0
DXF ScaleX= 1
DXF ScaleY= 10

--- K133-00-00.p02 (plan) ---

Plan Title=Floodway
Version=Version 3.0.1  Mar 2001
Short Identifier=Floodway0607
Geom File=g01
Flow File=f02
Subcritical Flow
K Sum by GR= 0
Std Step Tol= 0.01
Critical Tol= 0.01
Num of Std Step Trials= 20
Max Error Tol= 0.3
Flow Tol Ratio= 0.001
Split Flow NTrial= 30
Split Flow Tol= 0.02
Split Flow Ratio= 0.02
Log Output Level= 0
Friction Slope Method= 1
Unsteady Friction Slope Method= 2
Parabolic Critical Depth
Global Vel Dist= 0 , 0 , 0
Global Log Level= 0
CheckData=True
Encroach Param=-1 ,0,0, 2
Encroach River=K133-00-00
Encroach Reach=Reach - 1
Encroach Node=15135.0
       1    4953  5046.8
Encroach Node=14935.0
       1    4953  5046.8
Encroach Node=13605.3
       1  4959.9  5049.3
Encroach Node=12520.0
       1  4953.3  5055.3
Encroach Node=11921.
       1  4941.9  5041.9
Encroach Node=11823.8
       1  4928.4  5052.7
Encroach Node=11792.0
       1  4928.4  5052.7
Encroach Node=11760.2
       1  4928.4  5052.7
Encroach Node=11658.
       1  4951.3  5061.3
Encroach Node=10664.2
       1  4947.1  5049.9
Encroach Node=10269.2
       1  4951.2  5057.9
Encroach Node=9820.0
       1  4946.4  5056.7
Encroach Node=9043.0
       1  4950.1    5062
Encroach Node=8687.
       1  4942.6 5055.75
Encroach Node=8586.4
       1 4945.48 5053.98
Encroach Node=8576.3
       1 4945.48 5053.98
Encroach Node=8566.2
       1 4945.48 5053.98
Encroach Node=8391.3
       1 4946.35 5060.55
Encroach Node=8378.9
       1 4946.35 5060.55
Encroach Node=8366.4
       1 4946.35 5060.55
Encroach Node=8268.
       1  4939.8  5059.8
Encroach Node=7316.5
       1  4960.3  5058.6
Encroach Node=6669.
       1  4935.8  5081.9
Encroach Node=6561.4
       1  4908.1  5060.9
Encroach Node=6512.4
       1  4908.1  5060.9
Encroach Node=6463.4
       1  4908.1  5060.9
Encroach Node=6359.
       1    4958  5046.9
Encroach Node=4853.
       1  4950.4  5050.4
Encroach Node=4749.4
       1  4950.7  5039.2
Encroach Node=4739.3
       1  4950.7  5039.2
Encroach Node=4729.2
       1  4949.6  5040.2
Encroach Node=4575.0
       1  4927.8  5062.8
Encroach Node=4545.1
       1  4927.8  5062.8
Encroach Node=4515.1
       1  4927.8  5062.8
Encroach Node=4413.
       1  4944.7  5044.7
Encroach Node=3033.
       1  4964.5  5034.5
Encroach Node=2928.8
       1  4954.8  5041.5
Encroach Node=2918.7
       1  4954.8  5041.5
Encroach Node=2908.5
       1  4953.7  5044.6
Encroach Node=2694.7
       1  4928.3  5080.2
Encroach Node=2636.9
       1  4928.3  5080.2
Encroach Node=2579.1
       1  4928.3  5080.2
Encroach Node=2479.
       1  4943.1  5053.1
Encroach Node=1513.
       1  4956.8  5071.5
Encroach Node=1409.6
       13782.1153908.052
Encroach Node=1348.9
       13782.1153908.052
Encroach Node=1288.1
       13782.1153908.052
Encroach Node=1191.
       1    4953    5053
Encroach Node=260.
       1  4953.2  5043.2
Encroach Node=158.6
       1  4947.9  5050.8
Encroach Node=148.1
       1  4947.9  5050.8
Encroach Node=137.6
       1  4947.9  5050.8
Encroach Node=39
       1  4960.2  5040.2
Encroach Reach=K133-00-00_0001
Encroach Node=15135.0
       1    4953  5046.8
Encroach Node=14935.0
       1    4953  5046.8
Encroach Node=13605.3
       1  4959.9  5049.3
Encroach Node=12520.0
       1  4953.3  5055.3
Encroach Node=11921.
       1  4941.9  5041.9
Encroach Node=11823.8
       1  4928.4  5052.7
Encroach Node=11792.0
       1  4928.4  5052.7
Encroach Node=11760.2
       1  4928.4  5052.7
Encroach Node=11658.
       1  4951.3  5061.3
Encroach Node=10664.2
       1  4947.1  5049.9
Encroach Node=10269.2
       1  4951.2  5057.9
Encroach Node=9820.0
       1  4946.4  5056.7
Encroach Node=9043.0
       1  4950.1    5062
Encroach Node=8687.
       1  4942.6 5055.75
Encroach Node=8586.4
       1 4945.48 5053.98
Encroach Node=8576.3
       1 4945.48 5053.98
Encroach Node=8566.2
       1 4945.48 5053.98
Encroach Node=8391.3
       1 4946.35 5060.55
Encroach Node=8378.9
       1 4946.35 5060.55
Encroach Node=8366.4
       1 4946.35 5060.55
Encroach Node=8268.
       1  4939.8  5059.8
Encroach Node=7316.5
       1  4960.3  5058.6
Encroach Node=6669.
       1  4935.8  5081.9
Encroach Node=6561.4
       1  4908.1  5060.9
Encroach Node=6512.4
       1  4908.1  5060.9
Encroach Node=6463.4
       1  4908.1  5060.9
Encroach Node=6359.
       1    4958  5046.9
Encroach Node=4853.
       1  4950.4  5050.4
Encroach Node=4749.4
       1  4950.7  5039.2
Encroach Node=4739.3
       1  4950.7  5039.2
Encroach Node=4729.2
       1  4949.6  5040.2
Encroach Node=4575.0
       1  4927.8  5062.8
Encroach Node=4545.1
       1  4927.8  5062.8
Encroach Node=4515.1
       1  4927.8  5062.8
Encroach Node=4413.
       1  4944.7  5044.7
Encroach Node=3033.
       1  4964.5  5034.5
Encroach Node=2928.8
       1  4954.8  5041.5
Encroach Node=2918.7
       1  4954.8  5041.5
Encroach Node=2908.5
       1  4953.7  5044.6
Encroach Node=2694.7
       1  4928.3  5080.2
Encroach Node=2636.9
       1  4928.3  5080.2
Encroach Node=2579.1
       1  4928.3  5080.2
Encroach Node=2479.
       1  4943.1  5053.1
Encroach Node=1513.
       1  4956.8  5071.5
Encroach Node=1409.6
       13782.1153908.052
Encroach Node=1348.9
       13782.1153908.052
Encroach Node=1288.1
       13782.1153908.052
Encroach Node=1191.
       1    4953    5053
Encroach Node=260.
       1  4953.2  5043.2
Encroach Node=158.6
       1  4947.9  5050.8
Encroach Node=148.1
       1  4947.9  5050.8
Encroach Node=137.6
       1  4947.9  5050.8
Encroach Node=39
       1  4960.2  5040.2
Computation Interval=1HOUR
Output Interval=1HOUR
Run HTab= 0
Run UNet= 0
Run PostProcess= 0
UNET Theta= 1
UNET ZTol= 0.02
UNET ZSATol= 0.1
UNET MxIter= 20
UNET MaxInSteps= 20
UNET DtIC= 0
UNET DtMin= 0
UNET MaxCRTS= 20
UNET WFStab= 2
UNET SFStab= 1
UNET WFX= 1
UNET SFX= 1
UNET Convert EG Bridges=-1
UNET Use Existing IB Tables=-1
Instantaneous Interval=1HOUR
Write IC File= 0
Write Velocity= 0
Write Detailed= 0

--- K133-00-00.p01 (plan) ---

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Plan Title=FEMA Effective June 2007
Short Identifier=FEMAeff0607
Geom File=g01
Flow File=f01
Persistent XS Scale= 4385.18518518519 , 6192.59259259259 , 147.46062992126 , 120.836614173228 , 500 , 5
Encroach Param=-1 ,0,0, 0

--- K133-00-00.p04 (plan) ---

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Plan Title=Storage Routing
Short Identifier=Store_Rout
Geom File=g01
Flow File=f04
Encroach Param=-1 ,0,0, 0

--- K133-00-00.f02 (steady flow) ---

Flow Title=Floodway
Version=Version 3.0.1  Mar 2001
Number of Profiles= 2
Profile Names=1PCT_100yr, 1PCTFloodway_100yrFW
River Rch & RM=K133-00-00,K133-00-00_0001,15135.0
    1770    1770
River Rch & RM=K133-00-00,K133-00-00_0001,13605.3
    1840    1840
River Rch & RM=K133-00-00,K133-00-00_0001,12520.0
    1880    1880
River Rch & RM=K133-00-00,K133-00-00_0001,11823.8
    1950    1950
River Rch & RM=K133-00-00,K133-00-00_0001,10664.2
    2150    2150
River Rch & RM=K133-00-00,K133-00-00_0001,9043.0
    2240    2240
River Rch & RM=K133-00-00,K133-00-00_0001,8391.3
    2390    2390
River Rch & RM=K133-00-00,K133-00-00_0001,7316.5
    2500    2500
River Rch & RM=K133-00-00,K133-00-00_0001,6561.4
    2580    2580
River Rch & RM=K133-00-00,K133-00-00_0001,2928.8
    2647    2647
Boundary for River Rch & Prof#=K133-00-00,K133-00-00_0001, 1
Up Type= 0
Dn Type= 3
Dn Slope=.0037
Boundary for River Rch & Prof#=K133-00-00,K133-00-00_0001, 2
Up Type= 0
Dn Type= 3
Dn Slope=.0037
DSS Import GetInterval= 0
DSS Import GetPeak= 0
DSS Import FillOption= 0

--- K133-00-00.f01 (steady flow) ---

Flow Title=FEMA Effective June 2007
Version=Version 3.0.1  Mar 2001
Number of Profiles= 4
Profile Names=10PCT_10yr, 2PCT_50yr, 1PCT_100yr, 0.2PCT_500yr
River Rch & RM=K133-00-00,K133-00-00_0001,15135.0
     930    1560    1770    2520
River Rch & RM=K133-00-00,K133-00-00_0001,13605.3
     970    1610    1840    2620
River Rch & RM=K133-00-00,K133-00-00_0001,12520.0
    1000    1640    1880    2690
River Rch & RM=K133-00-00,K133-00-00_0001,11823.8
    1050    1700    1950    2800
River Rch & RM=K133-00-00,K133-00-00_0001,10664.2
    1160    1810    2150    3090
River Rch & RM=K133-00-00,K133-00-00_0001,9043.0
    1210    1860    2240    3220
River Rch & RM=K133-00-00,K133-00-00_0001,8391.3
    1290    1940    2390    3440
River Rch & RM=K133-00-00,K133-00-00_0001,7316.5
    1350    2000    2500    3600
River Rch & RM=K133-00-00,K133-00-00_0001,6561.4
    1380    2120    2580    3770
River Rch & RM=K133-00-00,K133-00-00_0001,2928.8
    1410    2222    2647    3900
Boundary for River Rch & Prof#=K133-00-00,K133-00-00_0001, 1
Up Type= 0
Dn Type= 3
Dn Slope=.0037
Boundary for River Rch & Prof#=K133-00-00,K133-00-00_0001, 2
Up Type= 0
Dn Type= 3
Dn Slope=.0037
Boundary for River Rch & Prof#=K133-00-00,K133-00-00_0001, 3
Up Type= 0
Dn Type= 3
Dn Slope=.0037
Boundary for River Rch & Prof#=K133-00-00,K133-00-00_0001, 4
Up Type= 0
Dn Type= 3
Dn Slope=.0037
DSS Import GetInterval= 0
DSS Import GetPeak= 0
DSS Import FillOption= 0

--- K133-00-00.f04 (steady flow) ---

Flow Title=Storage Routing
Version=Version 3.0.1  Mar 2001
Number of Profiles= 8
Profile Names=0.25*10% flood, 0.50*10%flood, 10% flood, 4% flood, 2% flood, 1% flood, 0.2%flood, 1.25*0.2% flood
River Rch & RM=K133-00-00,K133-00-00_0001,15135.0
      80     160     320     420     520     640     770     963
River Rch & RM=K133-00-00,K133-00-00_0001,13605.3
     198     395     790    1000    1240    1460    1820    2275
River Rch & RM=K133-00-00,K133-00-00_0001,12520.0
     335     670    1340    1670    2050    2360    2970    3713
River Rch & RM=K133-00-00,K133-00-00_0001,10269.2
     428     855    1710    2110    2560    2980    3790    4738
River Rch & RM=K133-00-00,K133-00-00_0001,4749.4
     500    1000    2000    2240    2880    3330    4250    5313
River Rch & RM=K133-00-00,K133-00-00_0001,1409.6
     618    1235    2470    2950    3370    3840    4920    6150
Boundary for River Rch & Prof#=K133-00-00,K133-00-00_0001, 1
Up Type= 0
Dn Type= 3
Dn Slope=.0037
Boundary for River Rch & Prof#=K133-00-00,K133-00-00_0001, 2
Up Type= 0
Dn Type= 3
Dn Slope=.0037
Boundary for River Rch & Prof#=K133-00-00,K133-00-00_0001, 3
Up Type= 0
Dn Type= 3
Dn Slope=.0037
Boundary for River Rch & Prof#=K133-00-00,K133-00-00_0001, 4
Up Type= 0
Dn Type= 3
Dn Slope=.0037
Boundary for River Rch & Prof#=K133-00-00,K133-00-00_0001, 5
Up Type= 0
Dn Type= 3
Dn Slope=.0037
Boundary for River Rch & Prof#=K133-00-00,K133-00-00_0001, 6
Up Type= 0
Dn Type= 3
Dn Slope=.0037
Boundary for River Rch & Prof#=K133-00-00,K133-00-00_0001, 7
Up Type= 0
Dn Type= 3
Dn Slope=.0037
Boundary for River Rch & Prof#=K133-00-00,K133-00-00_0001, 8
Up Type= 0
Dn Type= 3
Dn Slope=.0037
DSS Import GetInterval= 0
DSS Import GetPeak= 0
DSS Import FillOption= 0

--- K133-00-00.g01 (geometry) ---

Geom Title=K133-00-00 June 2007
Version=Version 3.0.1  Mar 2001

River Reach=K133-00-00      ,K133-00-00_0001
Reach XY= 30
      3058037.61      13937676.2        3058874.       13936505.
        3059763.       13935176.       3059818.8     13934957.71
        3060583.       13933843.      3060630.95     13933831.49
      3060942.58     13934018.12      3061017.23     13934006.84
      3061463.75       13933457.      3061630.08     13933354.06
      3061710.56     13933273.94       3061901.5       13932943.
      3062603.17     13932554.58      3063086.75       13932227.
      3063199.75       13932114.      3063269.84     13931895.73
      3063131.83      13931599.3       3063158.5       13931490.
      3063115.32     13931225.59      3063196.05     13931064.13
      3063709.94     13930321.94      3063759.25       13930278.
      3064261.16     13930213.44      3064415.67     13930156.15
      3065110.98     13929107.53      3065192.58     13929018.99
      3065958.58     13928840.84      3066712.97     13928705.67
      3066856.64     13928651.81      3067575.39      13927630.9

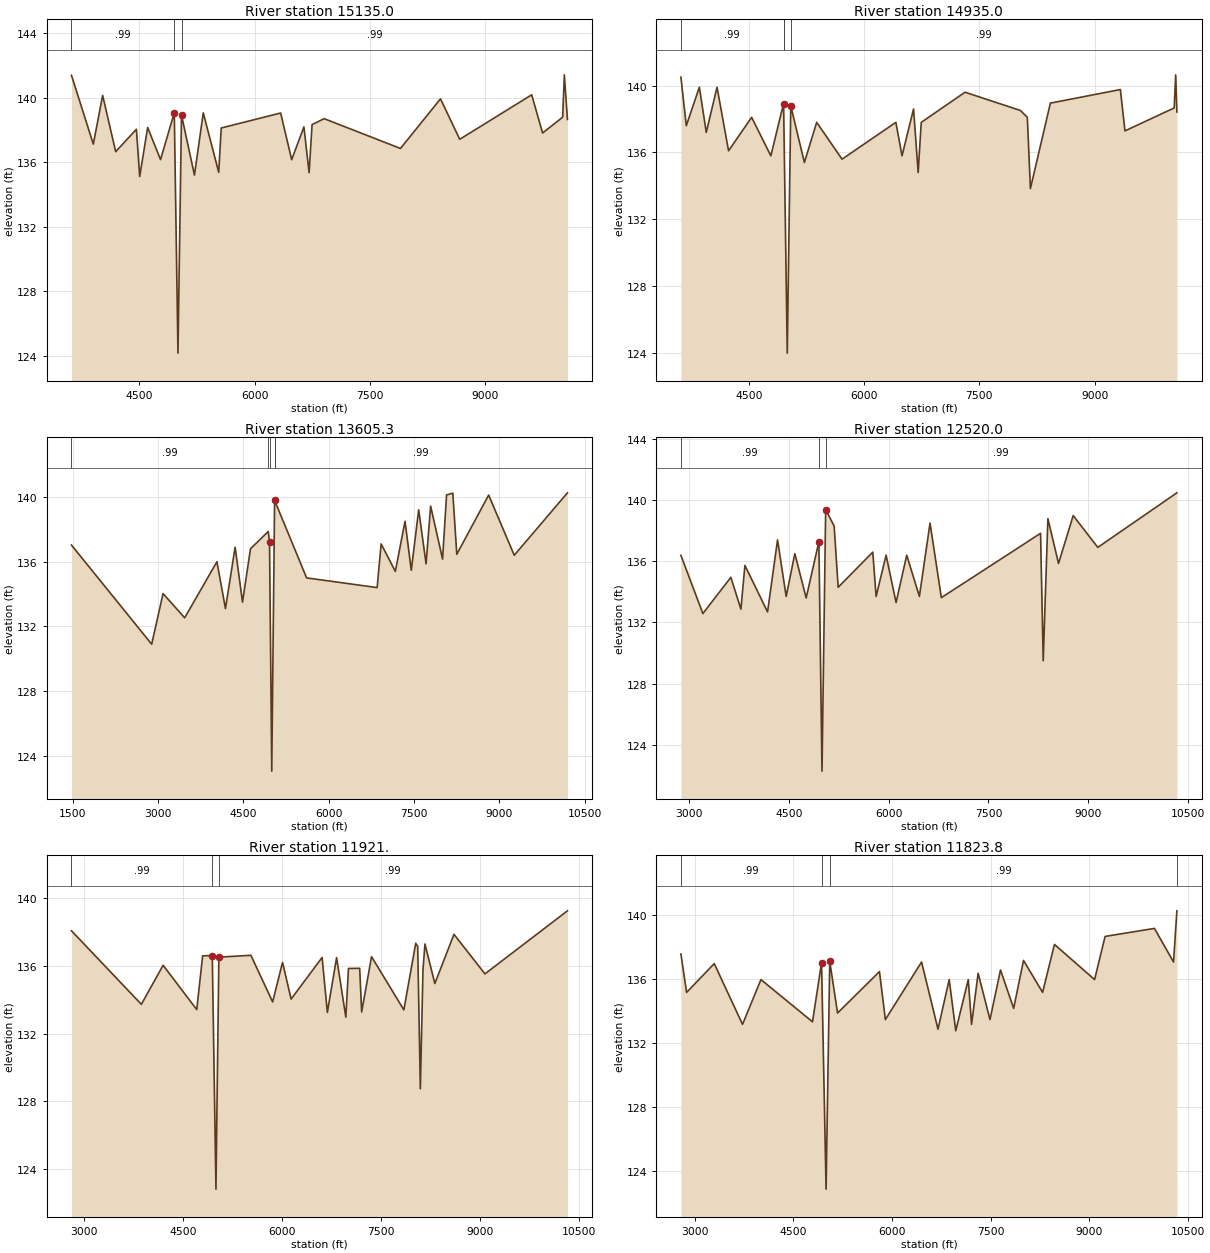
Type RM Length L Ch R = 1 ,15135.0 ,201,200,199
BEGIN DESCRIPTION:
Cross Section K133-00-00-X08a
This is an interpolated x-section.  Requested by PMT to cover the original LODS.
END DESCRIPTION:
XS GIS Cut Line= 4
      3059200.15      13938430.6      3058162.51      13937706.3
      3057964.14      13937569.9      3053770.89      13934948.4
#Sta/Elev= 30
  3615.5  141.39  3899.8  137.12  4021.2  140.14  4190.7  136.65  4460.2  138.04
  4503.1  135.11  4606.5  138.15  4774.2  136.16 4952.09  139.05    4953  139.05
  5000.8  124.15  5046.8  138.92  5215.4   135.2    5330  139.06    5531  135.37
  5563.7  138.12  6336.5  139.05  6479.9  136.15  6639.1  138.19  6706.6  135.35
  6745.2  138.33  6902.5   138.7  7895.1  136.85  8415.6  139.93  8665.9  137.42
    9602  140.18  9743.5  137.81 10004.8  138.79 10026.5  141.42   10067  138.65
#Mann= 3 ,-1 , 0
  3615.5     .99       0 4952.09     .04       0  5046.8     .99       0
Bank Sta=4953,5046.8
XS Rating Curve= 0
Exp/Cntr=.3,.1

Type RM Length L Ch R = 1 ,14935.0 ,1331.1,1329.7,1326.3
BEGIN DESCRIPTION:
Cross Section K133-00-00-X08
END DESCRIPTION:
XS GIS Cut Line= 4
      3059315.53     13938266.12      3058277.88     13937541.85
      3058079.51      13937405.4      3053886.27     13934783.87
#Sta/Elev= 30
  3617.4   140.5  3687.4   137.6  3857.4   139.9  3947.4   137.2  4087.4   139.9
  4237.4   136.1  4537.4   138.1  4787.4   135.8 4952.09  138.91    4953  138.91
  5000.8  124.01  5046.8  138.78  5223.6   135.4  5383.6   137.8  5713.6   135.6
  6413.6   137.8  6493.6   135.8  6643.6   138.6  6703.6   134.8  6743.6   137.8
  7313.6   139.6  8033.6  138.51  8123.6   138.1  8163.6  133.84  8423.6  138.95
  9333.6  139.76  9393.6  137.29 10033.6  138.66 10053.6  140.64 10068.9  138.42
#Mann= 4 ,-1 , 0
  3617.4     .99       0 4952.09     .04       0    4953     .04       0
  5046.8     .99       0
Bank Sta=4953,5046.8
XS Rating Curve= 0
Exp/Cntr=.3,.1

Type RM Length L Ch R = 1 ,13605.3 ,1081,1085.3,1088.6
BEGIN DESCRIPTION:
Cross Section K133-00-00-X07; left side spills to K131-02 11/12/2 VRR
END DESCRIPTION:
XS GIS Cut Line= 5
      3061597.44      13938668.8      3059768.06       13936890.
      3058986.37      13936413.3      3058835.86     13936322.23
      3054485.09     13933709.51
#Sta/Elev= 30
  1478.7  137.03  2888.7   130.9  3088.7  134.03  3468.7  132.53  4035.5     136
  4185.5   133.1  4355.5   136.9  4485.5   133.5  4625.5   136.8 4938.19  137.87
  4959.9  137.22  4999.2  123.05  5049.3  139.79 5049.91  139.79  5611.8     135
  6851.8   134.4  6921.8   137.1  7171.8   135.4  7341.8   138.5  7451.8  135.47
  7581.8  139.21  7711.8  135.87  7791.8  139.44  8001.8  136.16  8071.8  140.13
  8181.8  140.24  8251.8  136.46  8811.8  140.12  9261.8   136.4 10196.8  140.26
#Mann= 5 ,-1 , 0
  1478.7     .99       0 4938.19     .04       0  4959.9     .04       0
  5049.3     .04       0 5049.91     .99       0
Bank Sta=4959.9,5049.3
XS Rating Curve= 0
Exp/Cntr=.3,.1

Type RM Length L Ch R = 1 ,12520.0 ,589.9,599,601
BEGIN DESCRIPTION:
Cross Section K133-00-00-X06
END DESCRIPTION:
XS GIS Cut Line= 5
       3061338.6      13936590.1      3060517.01      13936214.7
      3059609.25     13935531.84      3059421.86     13935393.89
      3055160.23     13932453.16
#Sta/Elev= 30
    2881  136.39    3211  132.58    3631  134.95  3782.4  132.87  3842.4  135.73
  4182.4  132.69  4332.4   137.4  4462.4   133.7  4592.4   136.5  4762.4   133.6
  4953.3  137.28  5000.1  122.27  5055.3  139.38  5182.9   138.3  5242.9   134.3
  5762.9   136.6  5812.9   133.7  5962.9   136.4  6112.9   133.3  6272.9   136.4
  6462.9   133.7  6622.9   138.5  6792.9  133.62  8282.9  137.83  8322.9   129.5
  8392.9  138.79  8552.9  135.86  8772.9  138.99  9142.9  136.91 10330.6  140.48
#Mann= 3 ,-1 , 0
    2881     .99       0  4953.3     .04       0  5055.3     .99       0
Bank Sta=4953.3,5055.3
XS Rating Curve= 0
Exp/Cntr=.3,.1

Type RM Length L Ch R = 1 ,11921.  ,98,97.2,97
BEGIN DESCRIPTION:
K133-00-00-S6_KILRENNY-US - XS 4
END DESCRIPTION:
XS GIS Cut Line= 4
      3061516.12      13936349.9      3059928.36     13935044.18
        3059710.     13934893.17      3055334.17     13932081.87
#Sta/Elev= 30
  2806.2  138.08  3866.2  133.73  4196.2  136.04  4706.2  133.42  4796.2   136.6
  4941.9  136.61 4997.52   122.8  5041.9  136.52  5527.4  136.63  5857.4  133.87
  6007.4  136.21  6137.4  134.04  6607.4   136.5  6687.4  133.25  6827.4  136.49
  6967.4  132.97  7007.4  135.85  7177.4  135.86  7207.4  133.28  7357.4  136.55
  7847.4   133.4  8027.4  137.34  8057.4  137.16  8097.4  128.74  8137.4  135.77
  8167.4   137.3  8317.4  134.96  8607.4  137.87  9077.4  135.53 10328.5  139.26
#Mann= 3 ,-1 , 0
  2806.2     .99       0  4941.9     .04       0  5041.9     .99       0
Bank Sta=4941.9,5041.9
XS Rating Curve= 0
Exp/Cntr=.5,.3

Type RM Length L Ch R = 1 ,11823.8 ,63.1,63.6,65
BEGIN DESCRIPTION:
Upstream Section of Bridge/Culvert/Weir
END DESCRIPTION:
XS GIS Cut Line= 4
      3061571.49      13936270.2      3059983.73     13934964.44
      3059765.38     13934813.43      3055389.55     13932002.14
#Sta/Elev= 30
  2790.4  137.59  2877.2  135.19  3297.2  136.99  3727.2  133.19  4007.2  135.99
  4790.8  133.35  4928.4  137.05  4997.1  122.89  5052.7  137.13  5171.6   133.9
  5808.4  136.49  5898.4  133.49  6448.4  137.09  6698.4  132.89  6868.4  135.99
  6968.4  132.79  7158.4  135.99  7208.4  133.19  7308.4  136.39  7488.4  133.49
  7648.4  136.59  7848.4  134.19  7998.4  137.19  8288.4  135.19  8468.4  138.19
  9078.4  135.99  9238.4  138.69  9988.4  139.19 10278.4  137.09 10329.5  140.29
#Mann= 4 ,-1 , 0
  2790.4     .99       0  4928.4     .04       0  5052.7     .99       0
 10329.5     .99       0
#XS Ineff= 2 , 0
       0    4929     136    5058       0     136
Permanent Ineff=
       F       F
Bank Sta=4928.4,5052.7
XS Rating Curve= 0
Exp/Cntr=.5,.3

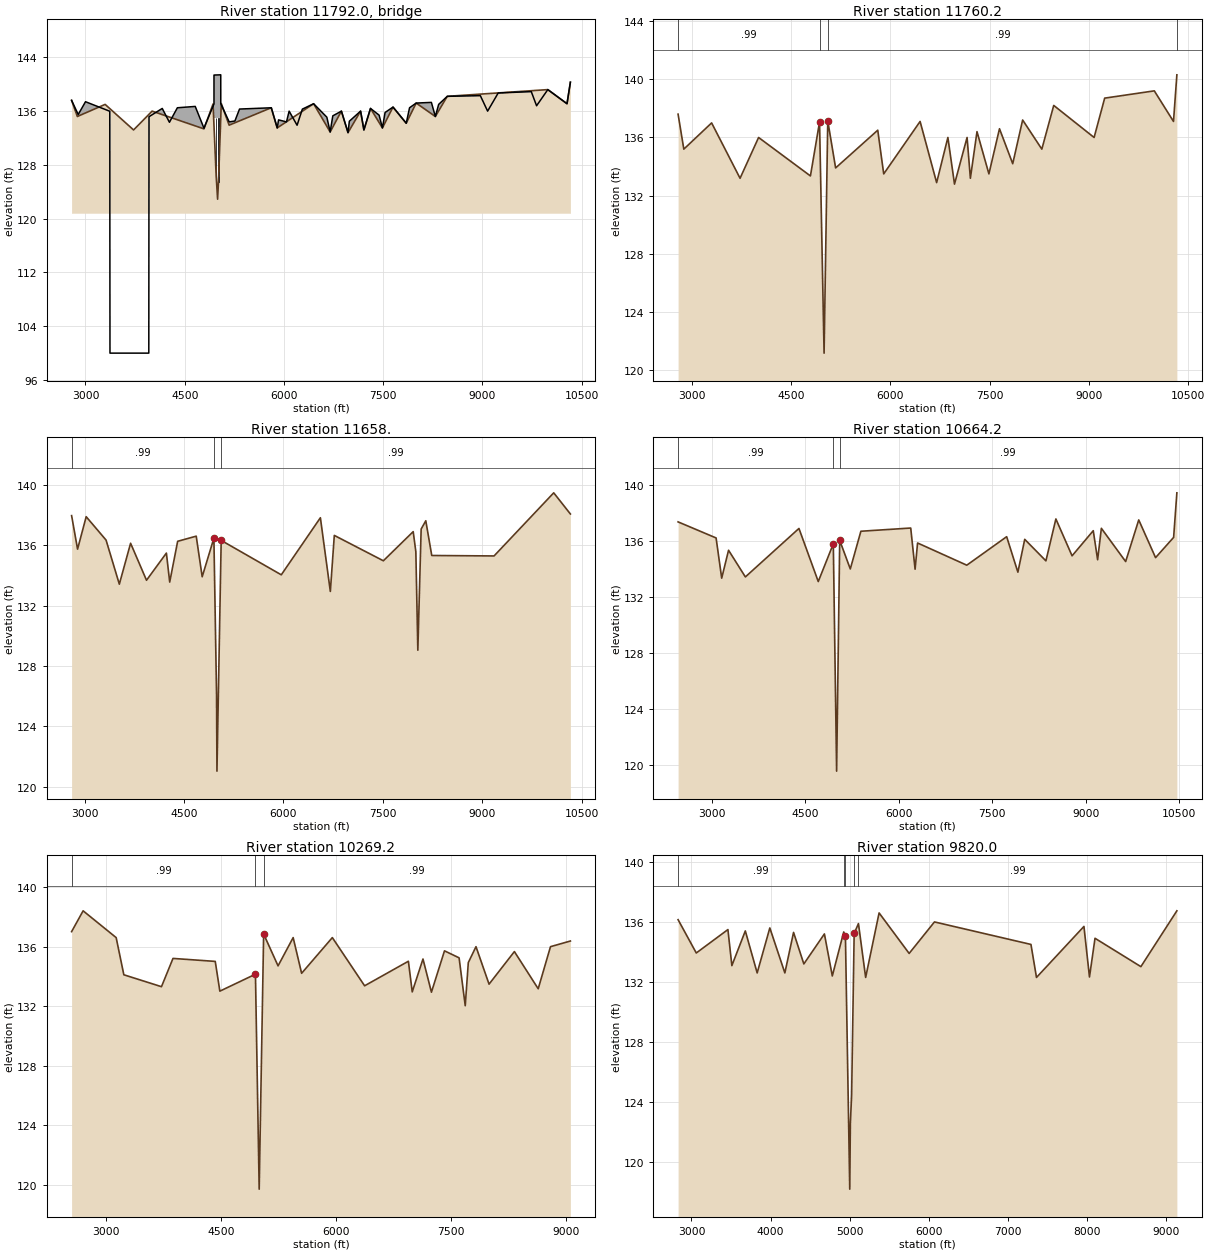
Type RM Length L Ch R = 3 ,11792.0 ,,,
BEGIN DESCRIPTION:
KILRENNY
Structure ID: K133-00-00-S6
Left side spills to K131-02 11/12/2 VRR
END DESCRIPTION:
Bridge Culvert--1,0,-1,-1, 0
Deck Dist Width WeirC Skew NumUp NumDn MinLoCord MaxHiCord MaxSubmerge Is_Ogee
10,41,2.6,0, 60, 60, , , .95, 0, ,,,
  2790.4  2890.4  3000.4  3367.2  3370.4  3957.2  3960.4  4160.4    4269    4389
    4659  4790.8 4942.29  4942.4  4942.9    4943  5043.7  5043.9 5044.79  5044.9
 5045.01  5172.3  5258.4  5328.4  5808.4  5898.4  5918.4  6038.4  6078.4  6198.4
  6278.4  6448.4  6648.4  6698.4  6738.4  6868.4  6968.4  6988.4  7158.4  7208.4
  7308.4  7438.4  7488.4  7528.4  7648.4  7848.4  7898.4  7998.4  8228.4  8288.4
  8338.4  8468.4  8968.4  9078.4  9238.4  9738.4  9818.4  9988.4 10278.4 10329.5
   137.6   135.5   137.4  135.98     100     100  135.17   136.4  134.34   136.5
   136.7  133.47  137.07  141.37  141.37  141.37   141.4   141.4   141.4   141.4
   137.1   134.4  134.53  136.31   136.5   133.5   134.7   134.4     136   133.9
   136.3   137.1   135.1   132.9   135.3     136   132.8   134.5     136   133.2
   136.4   135.4   133.5   135.8   136.6   134.2   136.5   137.2   137.3   135.2
     137   138.2   138.3     136   138.7   138.9   136.8   139.2   137.1   140.3
                                                                                
                                          134.98     135  134.72
                                                                                
                                                                                
                                                                                
                                                                                
  2790.4  2890.4  3000.4  3367.2  3370.4  3957.2  3960.4  4160.4    4269    4389
    4659  4790.8 4942.29  4942.4  4942.9    4943  5043.7  5043.9 5044.79  5044.9
 5045.01  5172.3  5258.4  5328.4  5808.4  5898.4  5918.4  6038.4  6078.4  6198.4
  6278.4  6448.4  6648.4  6698.4  6738.4  6868.4  6968.4  6988.4  7158.4  7208.4
  7308.4  7438.4  7488.4  7528.4  7648.4  7848.4  7898.4  7998.4  8228.4  8288.4
  8338.4  8468.4  8968.4  9078.4  9238.4  9738.4  9818.4  9988.4 10278.4 10329.5
   137.6   135.5   137.4  135.98     100     100  135.17   136.4  134.34   136.5
   136.7  133.47  137.07  141.37  141.37  141.37   141.4   141.4   141.4   141.4
   137.1   134.4  134.53  136.31   136.5   133.5   134.7   134.4     136   133.9
   136.3   137.1   135.1   132.9   135.3     136   132.8   134.5     136   133.2
   136.4   135.4   133.5   135.8   136.6   134.2   136.5   137.2   137.3   135.2
     137   138.2   138.3     136   138.7   138.9   136.8   139.2   137.1   140.3
                                                                                
                                          134.98     135  134.72
                                                                                
                                                                                
                                                                                
                                                                                
Pier Skew, UpSta & Num, DnSta & Num=  ,4975.601, 2 ,4975.601, 2 , 0 , 0 , 0 ,,
     1.3     1.3
  125.29  135.98
     1.3     1.3
  125.29  135.98
Pier Skew, UpSta & Num, DnSta & Num=  ,5010.2, 2 ,5010.2, 2 , 0 , 0 , 0 ,,
     1.3     1.3
  124.39  135.99
     1.3     1.3
  124.39  135.99
BR Coef= 1 , 1 , 1 ,1.25, 0 ,,,.8,0,2,0,
WSPro=,,,, 1 ,,,, 0 ,,,, 0 ,,,,-1 ,-1 ,-1 , 0 , 0 , 0 , 0 , 0
BR U #Sta/Elev= 30
  2790.4   137.6  2877.2   135.2  3297.2     137  3727.2   133.2  4007.2     136
  4790.8  133.36  4928.4  137.06  4975.6  126.36  4997.1   122.9  5010.2  125.47
  5052.7  137.14  5171.6  133.91  5808.4   136.5  5898.4   133.5  6448.4   137.1
  6698.4   132.9  6868.4     136  6968.4   132.8  7158.4     136  7208.4   133.2
  7308.4   136.4  7488.4   133.5  7648.4   136.6  7848.4   134.2  7998.4   137.2
  8288.4   135.2  8468.4   138.2  9988.4   139.2 10278.4   137.1 10329.5   140.3
BR U #Mann= 5
  2790.4     .99  4928.4    .015  4975.6     .04  5010.2    .015  5052.7     .99
BR U Banks=4928.4,5052.7
BR D #Sta/Elev= 30
  2790.4   137.6  2877.2   135.2  3297.2     137  3727.2   133.2  4007.2     136
  4790.8  133.36  4928.4  137.06  4975.6  124.67  4997.1  121.21  5010.2  123.78
  5052.7  137.14  5171.6  133.91  5808.4   136.5  5898.4   133.5  6448.4   137.1
  6698.4   132.9  6868.4     136  6968.4   132.8  7158.4     136  7208.4   133.2
  7308.4   136.4  7488.4   133.5  7648.4   136.6  7848.4   134.2  7998.4   137.2
  8288.4   135.2  8468.4   138.2  9988.4   139.2 10278.4   137.1 10329.5   140.3
BR D #Mann= 5
  2790.4     .99  4928.4    .015  4975.6     .04  5010.2    .015  5052.7     .99
BR D Banks=4928.4,5052.7
BC Design=,, 0 ,, 0 ,,,,,,

Type RM Length L Ch R = 1 ,11760.2 ,103,102.2,102
BEGIN DESCRIPTION:
Downstream Section of Bridge/Culvert/Weir
END DESCRIPTION:
XS GIS Cut Line= 4
      3061614.07     13936223.04      3060025.67     13934916.75
      3059806.35     13934765.07      3055430.23     13931953.59
#Sta/Elev= 30
  2790.4  137.59  2877.2  135.19  3297.2  136.99  3727.2  133.19  4007.2  135.99
  4790.8  133.35  4928.4  137.05  4997.1  121.19  5052.7  137.13  5171.6   133.9
  5808.4  136.49  5898.4  133.49  6448.4  137.09  6698.4  132.89  6868.4  135.99
  6968.4  132.79  7158.4  135.99  7208.4  133.19  7308.4  136.39  7488.4  133.49
  7648.4  136.59  7848.4  134.19  7998.4  137.19  8288.4  135.19  8468.4  138.19
  9078.4  135.99  9238.4  138.69  9988.4  139.19 10278.4  137.09 10329.5  140.29
#Mann= 4 ,-1 , 0
  2790.4     .99       0  4928.4     .04       0  5052.7     .99       0
 10329.5     .99       0
#XS Ineff= 2 , 0
       0  4932.8  133.47  5053.4       0     133
Permanent Ineff=
       F       F
Bank Sta=4928.4,5052.7
XS Rating Curve= 0
Exp/Cntr=.5,.3

Type RM Length L Ch R = 1 ,11658.  ,995.9,993.8,991.8
BEGIN DESCRIPTION:
K133-00-00-S6_KILRENNY-DS - XS 1
END DESCRIPTION:
XS GIS Cut Line= 4
      3061671.66      13936138.8      3060083.26     13934832.58
      3059863.94      13934680.9      3055487.82     13931869.43
#Sta/Elev= 30
  2804.7  137.96  2894.7  135.74  3024.7  137.89  3324.7  136.34  3524.7  133.42
  3694.7  136.13  3934.7  133.68  4234.7  135.48  4284.7  133.56  4404.7  136.26
  4684.7   136.6  4774.7  133.91  4951.3  136.47  4991.3  126.12  4997.4  121.04
  5061.3  136.32  5967.9  134.04  6557.9  137.82  6707.9  132.94  6767.9  136.65
  7507.9  134.97  7957.9   136.9  7997.9  135.57  8027.9  129.05  8077.9  137.07
  8147.9  137.62  8237.9  135.32  9177.9  135.29 10077.9  139.47 10329.3  138.07
#Mann= 3 ,-1 , 0
  2804.7     .99       0  4951.3     .04       0  5061.3     .99       0
Bank Sta=4951.3,5061.3
XS Rating Curve= 0
Exp/Cntr=.3,.1

Type RM Length L Ch R = 1 ,10664.2 ,323.2,395,454.1
BEGIN DESCRIPTION:
Cross Section K133-00-00-X05
END DESCRIPTION:
XS GIS Cut Line= 4
       3061982.1     13936004.99      3060577.91     13933962.67
      3060428.79     13933869.94      3055958.66     13930926.76
#Sta/Elev= 30
  2455.6  137.37  3065.6  136.22  3155.6  133.34  3265.6  135.34  3535.6  133.43
  4395.6   136.9  4705.6   133.1  4947.1   135.8  5000.3  119.53  5049.9  136.05
  5219.7     134  5389.7   136.7  6189.7  136.93  6259.7  133.98  6299.7  135.86
  7089.7  134.27  7729.7  136.31  7909.7  133.77  8019.7  136.12  8359.7  134.58
  8519.7  137.58  8779.7  134.94  9119.7  136.74  9189.7  134.66  9249.7  136.91
  9639.7  134.53  9849.7  137.51 10119.7  134.81 10409.7  136.26 10461.7  139.45
#Mann= 3 ,-1 , 0
  2455.6     .99       0  4947.1    .045       0  5049.9     .99       0
Bank Sta=4947.1,5049.9
XS Rating Curve= 0
Exp/Cntr=.3,.1

Type RM Length L Ch R = 1 ,10269.2 ,506.9,449.2,397
BEGIN DESCRIPTION:
Cross Section K133-00-00-X04
END DESCRIPTION:
XS GIS Cut Line= 5
      3062070.16     13935969.77       3060756.7     13934095.62
      3060875.34     13933876.71      3060757.72     13933550.54
      3058330.46     13930879.79
#Sta/Elev= 30
  2557.9     137  2707.9   138.4  3137.9   136.6  3237.9   134.1  3727.9   133.3
  3877.9   135.2  4427.9     135  4487.9     133  4951.2  134.14  4999.9  119.69
  5057.9  136.84  5245.5   134.7  5442.2   136.6  5552.2   134.2  5952.2   136.6
  6372.2  133.36  6942.2  135.01  6992.2  132.95  7132.2  135.16  7242.2  132.93
  7412.2  135.71  7602.2  135.24  7682.2  132.02  7722.2  134.92  7822.2  135.99
  7992.2  133.47  8322.2  135.66  8632.2  133.16  8792.2  135.99  9051.1  136.37
#Mann= 3 ,-1 , 0
  2557.9     .99       0  4951.2    .045       0  5057.9     .99       0
Bank Sta=4951.2,5057.9
XS Rating Curve= 0
Exp/Cntr=.3,.1

Type RM Length L Ch R = 1 ,9820.0  ,778,777,771.1
BEGIN DESCRIPTION:
Cross Section K133-00-00-X03
END DESCRIPTION:
XS GIS Cut Line= 4
      3062839.23     13935224.18      3061227.79     13933858.25
      3061122.25     13933783.76      3058553.55     13930633.22
#Sta/Elev= 30
  2830.5  136.15  3060.5  133.93  3460.5  135.49  3510.5  133.09  3680.5   135.4
  3830.5   132.6  3990.5   135.6  4180.5   132.6  4290.5   135.3  4420.5   133.2
  4680.5   135.2  4780.5   132.4 4924.82  135.33  4946.4  135.03    5001  118.19
  5008.8  122.58  5024.7  124.47  5056.7  135.23    5111  135.89  5202.1   132.3
  5372.1   136.6  5752.1   133.9  6072.1     136  7292.1   134.5  7362.1   132.3
  7962.1   135.7  8032.1  132.33  8102.1  134.91  8682.1  133.02  9137.1  136.74
#Mann= 5 ,-1 , 0
  2830.5     .99       0 4924.82    .045       0  4946.4     .04       0
  5056.7    .045       0    5111     .99       0
Bank Sta=4946.4,5056.7
XS Rating Curve= 0
Exp/Cntr=.3,.1

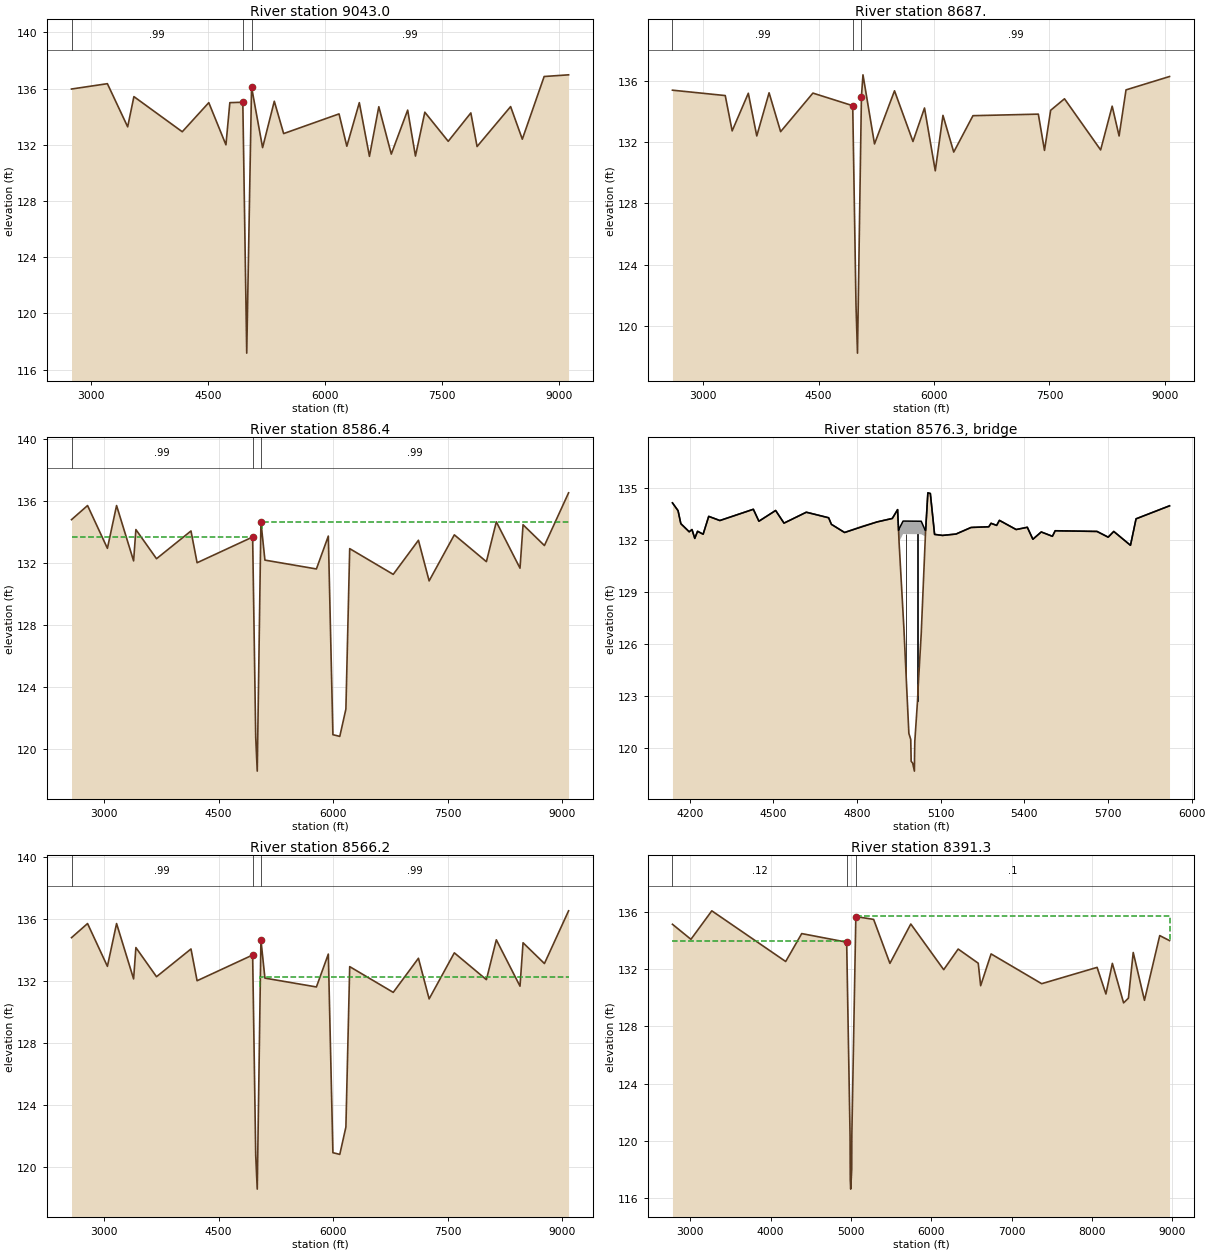
Type RM Length L Ch R = 1 ,9043.0  ,343.2,356,367.8
BEGIN DESCRIPTION:
Cross Section K133-00-00-X02
END DESCRIPTION:
XS GIS Cut Line= 4
      3062883.03     13935178.48      3061781.42     13933316.13
      3061632.26     13933222.29      3058670.79     13930484.47
#Sta/Elev= 30
  2753.7  135.97  3213.7  136.35  3473.7  133.28  3553.7  135.43  4173.7  132.93
  4513.7     135  4733.7     132  4783.7     135  4950.1  135.03  5000.2  117.18
    5062  136.11  5203.7   131.8  5353.7   135.1  5473.7   132.8  6183.7   134.2
  6283.7   131.9  6443.7     135  6573.7  131.18  6693.7  134.71  6853.7  131.34
  7063.7  134.47  7163.7   131.2  7283.7  134.32  7583.7  132.25  7873.7  134.27
  7953.7  131.88  8383.7  134.72  8533.7   132.4  8813.7  136.86  9126.8  136.98
#Mann= 3 ,-1 , 0
  2753.7     .99       0  4950.1     .04       0    5062     .99       0
Bank Sta=4950.1,5062
XS Rating Curve= 0
Exp/Cntr=.3,.1

Type RM Length L Ch R = 1 ,8687.   ,91.3,100.6,107.8
BEGIN DESCRIPTION:
K133-00-00-S4-2_PIPELINE-US - XS 4
END DESCRIPTION:
XS GIS Cut Line= 6
  3062932.98383213935122.9125018 3062739.5704015 13934509.512978
 3062006.213079313933146.0329219  3061846.29447113932910.2867186
 3061723.685420313932746.3740191 3058857.803050513930286.7753903
#Sta/Elev= 30
  2598.9  135.37  3285.1  135.02  3375.1  132.72  3585.1  135.17  3695.1  132.39
  3855.1   135.2  4005.1  132.67  4425.1  135.18  4942.6  134.36 4985.39  121.32
 5004.55  118.25 5055.75  134.95  5075.9  136.37  5225.9  131.87  5485.9  135.33
  5725.9  132.03  5875.9  134.21  6015.9  130.12  6115.9  133.73  6255.9  131.34
  6505.9  133.71  7355.9  133.81  7435.9  131.45  7515.9  134.06  7695.9  134.81
  8165.9  131.48  8315.9  134.33  8405.9  132.39  8495.9  135.39  9061.5  136.26
#Mann= 3 ,-1 , 0
  2598.9     .99       0  4942.6     .04       0 5055.75     .99       0
Bank Sta=4942.6,5055.75
XS Rating Curve= 0
Exp/Cntr=.5,.3

Type RM Length L Ch R = 1 ,8586.4  ,20,20.2,21
BEGIN DESCRIPTION:
Upstream Section of Bridge/Culvert/Weir
END DESCRIPTION:
XS GIS Cut Line= 5
      3062894.39      13935129.1       3062708.9     13934531.07
      3061928.26     13933012.41       3061839.6     13932912.94
      3058828.69     13930286.28
#Sta/Elev= 30
  2573.7  134.77  2783.7  135.68  3043.7  132.92  3163.7  135.68  3386.7  132.11
  3416.7  134.13  3686.7  132.25  4138.1  134.04  4218.1  131.99 4945.48  133.65
 4985.88  120.73 5005.78  118.55 5053.98  134.62 5106.28  132.16  5780.6  131.59
  5936.6  133.71  5996.6   120.9  6086.6  120.79  6166.6  122.55  6216.6   132.9
  6786.6  131.24  7116.6  133.44  7256.6  130.82  7586.6  133.79  8006.6  132.06
  8136.6  134.63  8446.6  131.64  8486.6  134.44  8766.6   133.1  9082.6   136.5
#Mann= 3 ,-1 , 0
  2573.7     .99       0 4945.48     .04       0 5053.98     .99       0
#XS Ineff= 2 , 0
       0 4935.48  133.65 5063.98       0  134.62
Permanent Ineff=
       F       F
Bank Sta=4945.48,5053.98
XS Rating Curve= 0
Exp/Cntr=.5,.3

Type RM Length L Ch R = 3 ,8576.3  ,,,
BEGIN DESCRIPTION:
PL1_K133-00-00-S4-2
END DESCRIPTION:
Bridge Culvert--1,0,-1,-1, 0
Deck Dist Width WeirC Skew NumUp NumDn MinLoCord MaxHiCord MaxSubmerge Is_Ogee
10,1,2.6,0, 49, 49, , , .95, 0, 1,1,,
  4138.1  4158.1  4168.1  4198.1  4208.1  4218.1  4228.1  4248.1  4268.1  4308.1
  4428.1  4448.1  4508.1  4538.1  4618.1  4698.1  4708.1 4755.28 4871.78 4926.48
 4945.48 4948.84 4950.68 4965.08 5030.18 5044.97    5046 5053.98 5062.88 5078.08
 5106.28 5154.88 5208.98 5272.58  5280.6  5300.6  5310.6  5370.6  5410.6  5430.6
  5460.6  5500.6  5510.6  5660.6  5700.6  5720.6  5780.6  5800.6  5920.6
  134.14  133.69  132.94  132.47   132.6  132.09   132.5  132.33  133.36  133.12
  133.77  133.08   133.7  132.97   133.6  133.28   132.9  132.43  133.04  133.24
  133.75  132.55  132.64  133.09  133.08  132.54  132.55  134.72  134.68  132.32
  132.26  132.34  132.72  132.76  132.96  132.84  133.13   132.6  132.73  132.04
  132.46  132.21  132.53  132.49  132.16  132.49  131.69  133.22  133.97
  134.14  133.69  132.94  132.47   132.6  132.09   132.5  132.33  133.36  133.12
  133.77  133.08   133.7  132.97   133.6  133.28   132.9  132.43  133.04  133.24
  133.75  132.55  131.89  132.34  132.33   132.2  132.55  134.72  134.68  132.32
  132.26  132.34  132.72  132.76  132.96  132.84  133.13   132.6  132.73  132.04
  132.46  132.21  132.53  132.49  132.16  132.49  131.69  133.22  133.97
  4138.1  4158.1  4168.1  4198.1  4208.1  4218.1  4228.1  4248.1  4268.1  4308.1
  4428.1  4448.1  4508.1  4538.1  4618.1  4698.1  4708.1 4755.28 4871.78 4926.48
 4945.48 4948.84 4950.68 4965.08 5030.18 5044.97    5046 5053.98 5062.88 5078.08
 5106.28 5154.88 5208.98 5272.58  5280.6  5300.6  5310.6  5370.6  5410.6  5430.6
  5460.6  5500.6  5510.6  5660.6  5700.6  5720.6  5780.6  5800.6  5920.6
  134.14  133.69  132.94  132.47   132.6  132.09   132.5  132.33  133.36  133.12
  133.77  133.08   133.7  132.97   133.6  133.28   132.9  132.43  133.04  133.24
  133.75  132.55  132.64  133.09  133.08  132.54  132.55  134.72  134.68  132.32
  132.26  132.34  132.72  132.76  132.96  132.84  133.13   132.6  132.73  132.04
  132.46  132.21  132.53  132.49  132.16  132.49  131.69  133.22  133.97
  134.14  133.69  132.94  132.47   132.6  132.09   132.5  132.33  133.36  133.12
  133.77  133.08   133.7  132.97   133.6  133.28   132.9  132.43  133.04  133.24
  133.75  132.55  131.89  132.34  132.33   132.2  132.55  134.72  134.68  132.32
  132.26  132.34  132.72  132.76  132.96  132.84  133.13   132.6  132.73  132.04
  132.46  132.21  132.53  132.49  132.16  132.49  131.69  133.22  133.97
Pier Skew, UpSta & Num, DnSta & Num=  ,4976.8, 2 ,4976.8, 2 , 0 , 0 , 0 ,,
      .8      .8
  122.77  133.34
      .8      .8
  122.77  133.34
Pier Skew, UpSta & Num, DnSta & Num=  ,5016.9, 2 ,5016.9, 2 , 0 , 0 , 0 ,,
      .8      .8
   121.6  133.33
      .8      .8
   121.6  133.33
BR Coef= 1 , 1 , 1 ,1.25, 0 ,,,.8,0,2,0,
WSPro=,,,, 1 ,,,, 0 ,,,, 0 ,,,,-1 ,-1 ,-1 , 0 , 0 , 0 , 0 , 0
BR U #Sta/Elev= 71
  4138.1  134.14  4158.1  133.69  4168.1  132.94  4198.1  132.47  4208.1   132.6
  4218.1  132.09  4228.1   132.5  4248.1  132.33  4268.1  133.36  4308.1  133.12
  4428.1  133.77  4448.1  133.08  4508.1   133.7  4538.1  132.97  4618.1   133.6
  4698.1  133.28  4708.1   132.9 4755.28  132.43 4816.58  132.77 4871.78  133.04
 4926.48  133.24 4945.11  133.74 4945.48  133.75 4948.84  132.55 4950.38     132
 4950.49  131.96 4950.58  131.93 4950.68  131.89 4965.08  127.75 4968.28  126.83
 4976.78   123.9 4985.88  120.83 4992.58  120.48 4993.78  119.53 4994.08  119.22
 4999.48  119.11 5005.78  118.65 5006.18  119.52 5007.18  120.37 5016.88   122.7
 5019.48   123.6 5030.08  126.56 5030.18   126.6 5044.97   132.2 5045.08  132.24
 5045.18  132.28 5045.28  132.31 5045.78  132.48    5046  132.55 5053.98  134.72
 5062.88  134.68 5078.08  132.32 5106.28  132.26 5154.88  132.34 5208.98  132.72
 5272.58  132.76  5280.6  132.96  5300.6  132.84  5310.6  133.13  5370.6   132.6
  5410.6  132.73  5430.6  132.04  5460.6  132.46  5500.6  132.21  5510.6  132.53
  5660.6  132.49  5700.6  132.16  5720.6  132.49  5780.6  131.69  5800.6  133.22
  5920.6  133.97
BR U #Mann= 3
  4138.1     .99 4945.48     .04 5053.98     .99
BR U Banks=4945.48,5053.98
BR D #Sta/Elev= 71
  4138.1  134.14  4158.1  133.69  4168.1  132.94  4198.1  132.47  4208.1   132.6
  4218.1  132.09  4228.1   132.5  4248.1  132.33  4268.1  133.36  4308.1  133.12
  4428.1  133.77  4448.1  133.08  4508.1   133.7  4538.1  132.97  4618.1   133.6
  4698.1  133.28  4708.1   132.9 4755.28  132.43 4816.58  132.77 4871.78  133.04
 4926.48  133.24 4945.11  133.74 4945.48  133.75 4948.84  132.55 4950.38     132
 4950.49  131.96 4950.58  131.93 4950.68  131.89 4965.08  127.75 4968.28  126.83
 4976.78   123.9 4985.88  120.83 4992.58  120.48 4993.78  119.53 4994.08  119.22
 4999.48  119.11 5005.78  118.65 5006.18  119.52 5007.18  120.37 5016.88   122.7
 5019.48   123.6 5030.08  126.56 5030.18   126.6 5044.97   132.2 5045.08  132.24
 5045.18  132.28 5045.28  132.31 5045.78  132.48    5046  132.55 5053.98  134.72
 5062.88  134.68 5078.08  132.32 5106.28  132.26 5154.88  132.34 5208.98  132.72
 5272.58  132.76  5280.6  132.96  5300.6  132.84  5310.6  133.13  5370.6   132.6
  5410.6  132.73  5430.6  132.04  5460.6  132.46  5500.6  132.21  5510.6  132.53
  5660.6  132.49  5700.6  132.16  5720.6  132.49  5780.6  131.69  5800.6  133.22
  5920.6  133.97
BR D #Mann= 3
  4138.1     .99 4945.48     .04 5053.98     .99
BR D Banks=4945.48,5053.98
BC Design=,, 0 ,, 0 ,,,,,,

Type RM Length L Ch R = 1 ,8566.2  ,173.2,174.9,176.6
BEGIN DESCRIPTION:
Downstream Section of Bridge/Culvert/Weir
END DESCRIPTION:
XS GIS Cut Line= 6
      3062966.52     13935102.41      3062809.69     13934468.56
      3062018.09     13932956.16      3061946.42     13932832.47
      3061829.26     13932658.21      3058923.52      13930215.6
#Sta/Elev= 30
  2573.7  134.77  2783.7  135.68  3043.7  132.92  3163.7  135.68  3386.7  132.11
  3416.7  134.13  3686.7  132.25  4138.1  134.04  4218.1  131.99 4945.48  133.65
 4985.88  120.73 5005.78  118.55 5053.98  134.62 5106.28  132.16  5780.6  131.59
  5936.6  133.71  5996.6   120.9  6086.6  120.79  6166.6  122.55  6216.6   132.9
  6786.6  131.24  7116.6  133.44  7256.6  130.82  7586.6  133.79  8006.6  132.06
  8136.6  134.63  8446.6  131.64  8486.6  134.44  8766.6   133.1  9082.6   136.5
#Mann= 3 ,-1 , 0
  2573.7     .99       0 4945.48     .04       0 5053.98     .99       0
#XS Ineff= 2 , 0
       0  4950.7   131.9 5044.97       0   132.2
Permanent Ineff=
       F       F
Bank Sta=4945.48,5053.98
XS Rating Curve= 0
Exp/Cntr=.5,.3

Type RM Length L Ch R = 1 ,8391.3  ,23,24.9,26
BEGIN DESCRIPTION:
Upstream Section of Bridge/Culvert/Weir
END DESCRIPTION:
XS GIS Cut Line= 5
      3063226.25     13934755.76      3062175.72     13932886.95
      3062104.21      13932749.5      3062040.99     13932628.01
      3059593.44     13929788.31
#Sta/Elev= 30
    2777  135.14    3007  134.09    3267  136.08    4187  132.54  4386.6  134.49
 4946.35  133.89 4988.65  120.37 4991.15  117.31 4996.55  116.64 5009.35  118.02
 5010.65  120.37 5060.55  135.68  5282.3  135.48  5484.8  132.41  5744.8  135.16
  6154.8  131.97  6334.8  133.41  6584.8  132.42  6614.8  130.85  6744.8  133.07
  7374.8  130.99  8064.8  132.13  8174.8  130.27  8254.8  132.41  8394.8  129.65
  8454.8  129.98  8514.8  133.17  8654.8  129.83  8844.8  134.35  8966.7     134
#Mann= 3 ,-1 , 0
    2777     .12       0 4946.35     .04       0 5060.55      .1       0
#XS Ineff= 2 , 0
       0 4936.35     134 5070.55       0   135.7
Permanent Ineff=
       F       F
Bank Sta=4946.35,5060.55
XS Rating Curve= 0
Exp/Cntr=.5,.3