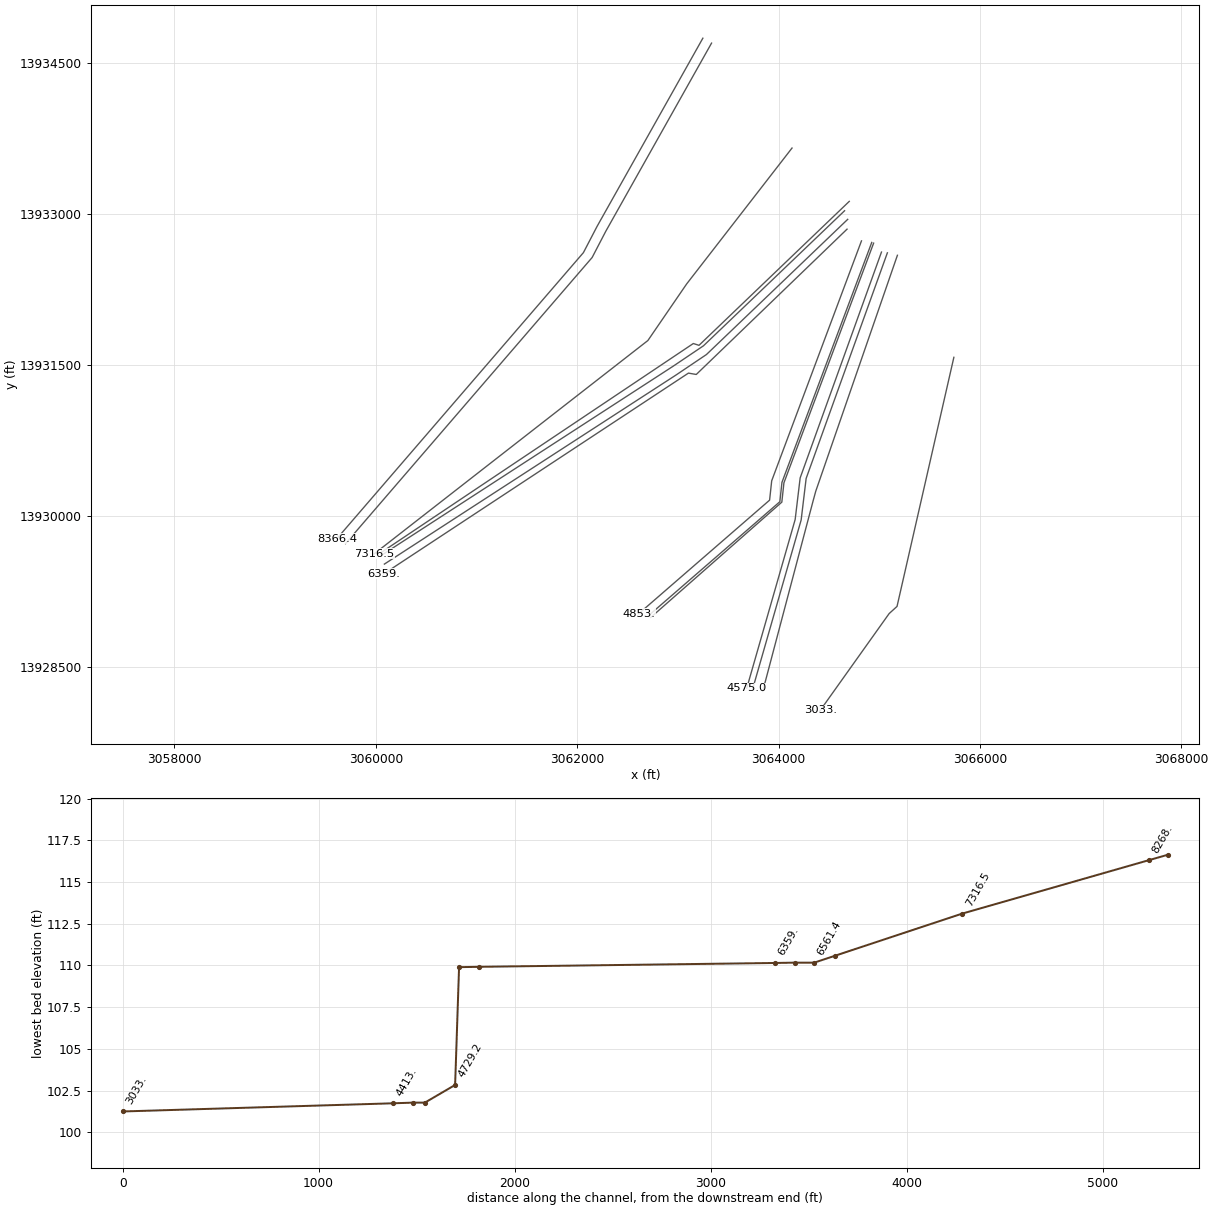
HEC-RAS study K133-00-00.prj: K133-00-00

--- K133-00-00.g01 (geometry) --- (continued)

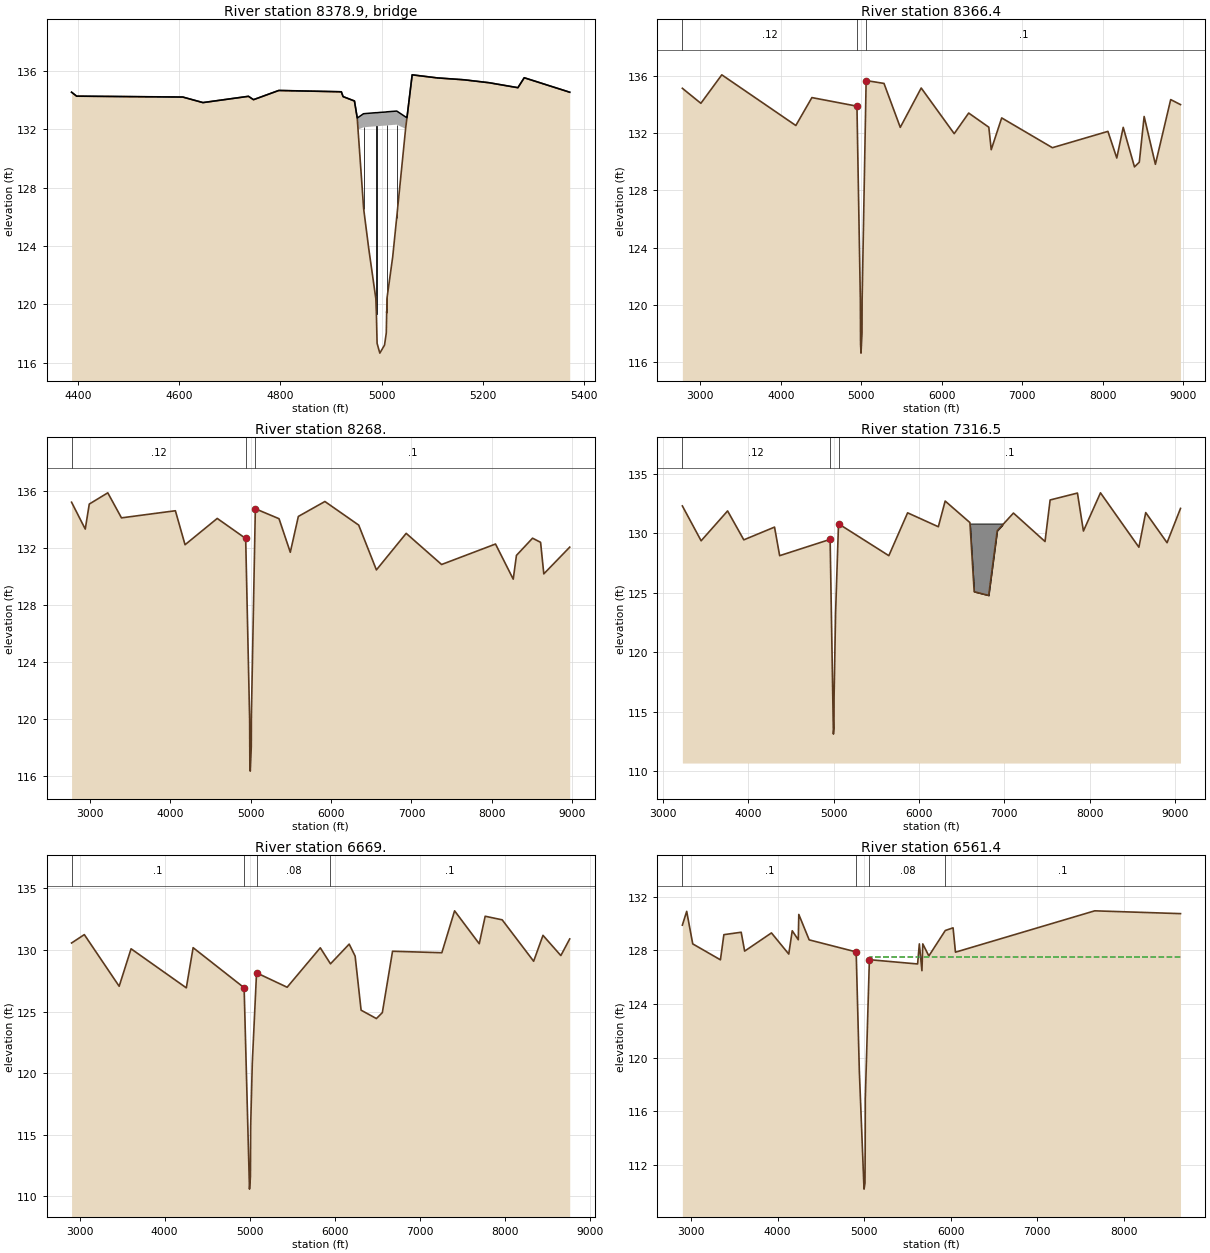
Type RM Length L Ch R = 3 ,8378.9  ,,,
BEGIN DESCRIPTION:
PL1_K133-00-00-S4-1
END DESCRIPTION:
Bridge Culvert--1,0,-1,-1, 0
Deck Dist Width WeirC Skew NumUp NumDn MinLoCord MaxHiCord MaxSubmerge Is_Ogee
10,1,2.6,0, 43, 43, , , .95, 0, 1,1,,
  4386.6  4396.6  4606.6  4646.6  4736.6  4746.6  4796.6  4920.4 4923.85 4946.35
 4951.85 4951.96 4952.06 4952.15 4953.44 4964.25 4964.55 4974.55 4988.65 4989.75
 4991.15 4996.55 5005.85 5009.35 5010.15 5010.25 5010.65 5022.05 5029.85 5030.15
 5047.55 5048.34 5048.45 5048.55 5050.19 5050.29 5060.55 5109.95 5163.25 5212.65
 5269.75  5282.3  5372.3
  134.52  134.25  134.19  133.81  134.24  134.01  134.64  134.55  134.22  133.92
  132.76  132.76  132.76  132.76  132.79  133.05  133.05  133.08  133.12  133.12
  133.12  133.14  133.16  133.17  133.18  133.18  133.18  133.21  133.23  133.23
  132.83  132.81  132.81  132.81  132.78  132.78  135.71   135.5  135.37  135.17
  134.83  135.51  134.52
  134.52  134.25  134.19  133.81  134.24  134.01  134.64  134.55  134.22  133.92
  132.76   132.7  132.65  132.61  131.96  132.12  132.12  132.15  132.19  132.19
  132.19  132.21  132.23  132.24  132.25  132.25  132.25  132.28   132.3   132.3
  132.02  132.24  132.27   132.3  132.75  132.78  135.71   135.5  135.37  135.17
  134.83  135.51  134.52
  4386.6  4396.6  4606.6  4646.6  4736.6  4746.6  4796.6  4920.4 4923.85 4946.35
 4951.85 4951.96 4952.06 4952.15 4953.44 4964.25 4964.55 4974.55 4988.65 4989.75
 4991.15 4996.55 5005.85 5009.35 5010.15 5010.25 5010.65 5022.05 5029.85 5030.15
 5047.55 5048.34 5048.45 5048.55 5050.19 5050.29 5060.55 5109.95 5163.25 5212.65
 5269.75  5282.3  5372.3
  134.52  134.25  134.19  133.81  134.24  134.01  134.64  134.55  134.22  133.92
  132.76  132.76  132.76  132.76  132.79  133.05  133.05  133.08  133.12  133.12
  133.12  133.14  133.16  133.17  133.18  133.18  133.18  133.21  133.23  133.23
  132.83  132.81  132.81  132.81  132.78  132.78  135.71   135.5  135.37  135.17
  134.83  135.51  134.52
  134.52  134.25  134.19  133.81  134.24  134.01  134.64  134.55  134.22  133.92
  132.76   132.7  132.65  132.61  131.96  132.12  132.12  132.15  132.19  132.19
  132.19  132.21  132.23  132.24  132.25  132.25  132.25  132.28   132.3   132.3
  132.02  132.24  132.27   132.3  132.75  132.78  135.71   135.5  135.37  135.17
  134.83  135.51  134.52
Pier Skew, UpSta & Num, DnSta & Num=  ,4964.6, 2 ,4964.6, 2 , 0 , 0 , 0 ,,
      .7      .7
  125.46  133.12
      .7      .7
  125.46  133.12
Pier Skew, UpSta & Num, DnSta & Num=  ,4989.8, 2 ,4989.8, 2 , 0 , 0 , 0 ,,
      .7      .7
  117.88  133.19
      .7      .7
  117.88  133.19
Pier Skew, UpSta & Num, DnSta & Num=  ,5010.2, 2 ,5010.2, 2 , 0 , 0 , 0 ,,
      .7      .7
  117.87  133.25
      .7      .7
  117.87  133.25
Pier Skew, UpSta & Num, DnSta & Num=  ,5029.9, 2 ,5029.9, 2 , 0 , 0 , 0 ,,
      .7      .7
  124.79   133.3
      .7      .7
  124.79   133.3
BR Coef= 1 , 1 , 1 ,1.25, 0 ,,,.8,0,2,0,
WSPro=,,,, 1 ,,,, 0 ,,,, 0 ,,,,-1 ,-1 ,-1 , 0 , 0 , 0 , 0 , 0
BR U #Sta/Elev= 43
  4386.6  134.52  4396.6  134.25  4606.6  134.19  4646.6  133.81  4736.6  134.24
  4746.6  134.01  4796.6  134.64  4920.4  134.55 4923.85  134.22 4946.35  133.92
 4951.85  132.76 4951.96   132.7 4952.06  132.65 4952.15  132.61 4953.44  131.96
 4964.25   126.7 4964.55  126.55 4974.55  123.84 4988.65   120.4 4989.75   119.4
 4991.15  117.34 4996.55  116.67 5005.85  117.22 5009.35  118.05 5010.15  119.51
 5010.25  119.43 5010.65   120.4 5022.05  123.26 5029.85  125.91 5030.15  126.01
 5047.55  132.02 5048.34  132.24 5048.45  132.27 5048.55   132.3 5050.19  132.75
 5050.29  132.78 5060.55  135.71 5109.95   135.5 5163.25  135.37 5212.65  135.17
 5269.75  134.83  5282.3  135.51  5372.3  134.52
BR U #Mann= 3
  4386.6     .12 4946.35     .04 5060.55      .1
BR U Banks=4946.35,5060.55
BR D #Sta/Elev= 43
  4386.6  134.52  4396.6  134.25  4606.6  134.19  4646.6  133.81  4736.6  134.24
  4746.6  134.01  4796.6  134.64  4920.4  134.55 4923.85  134.22 4946.35  133.92
 4951.85  132.76 4951.96   132.7 4952.06  132.65 4952.15  132.61 4953.44  131.96
 4964.25   126.7 4964.55  126.55 4974.55  123.84 4988.65   120.4 4989.75   119.4
 4991.15  117.34 4996.55  116.67 5005.85  117.22 5009.35  118.05 5010.15  119.51
 5010.25  119.43 5010.65   120.4 5022.05  123.26 5029.85  125.91 5030.15  126.01
 5047.55  132.02 5048.34  132.24 5048.45  132.27 5048.55   132.3 5050.19  132.75
 5050.29  132.78 5060.55  135.71 5109.95   135.5 5163.25  135.37 5212.65  135.17
 5269.75  134.83  5282.3  135.51  5372.3  134.52
BR D #Mann= 3
  4386.6     .12 4946.35     .04 5060.55      .1
BR D Banks=4946.35,5060.55
BC Design=,, 0 ,, 0 ,,,,,,

Type RM Length L Ch R = 1 ,8366.4  ,99.2,98.4,97
BEGIN DESCRIPTION:
Downstream Section of Bridge/Culvert/Weir
END DESCRIPTION:
XS GIS Cut Line= 4
      3063248.04     13934743.51      3062197.71     13932875.05
      3062061.83     13932613.89      3059612.37     13929771.99
#Sta/Elev= 30
    2777  135.14    3007  134.09    3267  136.08    4187  132.54  4386.6  134.49
 4946.35  133.89 4988.65  120.37 4991.15  117.31 4996.55  116.64 5009.35  118.02
 5010.65  120.37 5060.55  135.68  5282.3  135.48  5484.8  132.41  5744.8  135.16
  6154.8  131.97  6334.8  133.41  6584.8  132.42  6614.8  130.85  6744.8  133.07
  7374.8  130.99  8064.8  132.13  8174.8  130.27  8254.8  132.41  8394.8  129.65
  8454.8  129.98  8514.8  133.17  8654.8  129.83  8844.8  134.35  8966.7     134
#Mann= 3 ,-1 , 0
    2777     .12       0 4946.35     .04       0 5060.55      .1       0
#XS Ineff= 2 , 0
       0    4943     132    5057       0     132
Permanent Ineff=
       F       F
Bank Sta=4946.35,5060.55
XS Rating Curve= 0
Exp/Cntr=.5,.3

Type RM Length L Ch R = 1 ,8268.   ,954.3,951.5,947.1
BEGIN DESCRIPTION:
K133-00-00-S4-1_PIPELINE-DS - XS 1
END DESCRIPTION:
XS GIS Cut Line= 4
      3063334.42      13934694.7       3062284.1     13932826.32
      3062148.21     13932565.16      3059698.75     13929723.26
#Sta/Elev= 30
  2776.4  135.22  2946.4  133.33  2996.4  135.09  3226.4  135.88  3396.4  134.12
  4066.4  134.62  4186.4  132.23  4586.4  134.08  4939.8  132.67 4989.03  119.93
 4991.48  116.96 4996.76  116.31 5009.48  118.02 5010.77   120.2  5059.8  134.76
  5354.2  134.06  5494.2   131.7  5594.2  134.22  5924.2  135.27  6344.2  133.61
  6564.2  130.46  6934.2  133.03  7374.2  130.84  8044.2  132.28  8264.2  129.81
  8304.2  131.48  8504.2  132.69  8604.2   132.4  8644.2  130.18  8966.1  132.06
#Mann= 3 ,-1 , 0
  2776.4     .12       0  4939.8     .04       0  5059.8      .1       0
Bank Sta=4939.8,5059.8
XS Rating Curve= 0
Exp/Cntr=.3,.1

Type RM Length L Ch R = 1 ,7316.5  ,683.1,647.5,630.2
BEGIN DESCRIPTION:
Cross Section K133-00-00-X01
END DESCRIPTION:
XS GIS Cut Line= 5
      3064133.69     13933652.44       3063087.3     13932302.95
      3063007.54     13932186.56      3062701.96      13931740.6
      3059982.64     13929621.19
#Sta/Elev= 30
  3228.9  132.28  3448.9  129.35  3758.9  131.86  3948.9  129.43  4308.9   130.5
  4368.9   128.1  4960.3  129.47  4998.8  113.11  5005.3  113.62  5006.5  116.16
  5024.1  123.24  5058.6  130.78  5648.3   128.1  5868.3   131.7  6228.3  130.53
  6308.3  132.69  6598.3  130.88  6648.3  125.07  6818.3  124.76  6918.3  130.19
  7108.3  131.68  7478.3  129.29  7538.3  132.78  7858.3  133.36  7928.3  130.17
  8128.3  133.38  8578.3  128.81  8658.3  131.72  8908.3  129.19  9065.9  132.07
#Mann= 3 ,-1 , 0
  3228.9     .12       0  4960.3     .04       0  5058.6      .1       0
#Block Obstruct= 2 ,-1
    6598 6978.53   130.8    6979    6980     110
Bank Sta=4960.3,5058.6
XS Rating Curve= 0
Exp/Cntr=.3,.1

Type RM Length L Ch R = 1 ,6669.   ,57.4,107.6,137.2
BEGIN DESCRIPTION:
K133-00-00-S4_LOUETTA-US - XS 4
END DESCRIPTION:
XS GIS Cut Line= 4
      3064702.28      13933122.8      3063209.67     13931692.98
      3063153.36       13931711.      3060050.26     13929633.34
#Sta/Elev= 30
  2905.8  130.56  3055.8  131.24  3465.8  127.05  3605.8  130.09  4255.8  126.92
  4335.8  130.18  4935.8  126.93 4998.97  110.59 5009.92  111.58  5012.8   115.7
  5031.9  120.82  5081.9  128.14  5441.9  126.97  5831.9  130.17  5951.9  128.87
  6171.9  130.47  6241.9  129.49  6311.9  125.11  6491.9  124.43  6561.9  124.91
  6681.9  129.89  7261.9  129.77  7411.9  133.17  7701.9   130.5  7771.9  132.73
  7971.9  132.44  8341.9  129.08  8451.9  131.18  8661.9  129.54  8766.3  130.89
#Mann= 4 ,-1 , 0
  2905.8      .1       0  4935.8     .04       0  5081.9     .08       0
  5951.9      .1       0
Bank Sta=4935.8,5081.9
XS Rating Curve= 0
Exp/Cntr=.5,.3

Type RM Length L Ch R = 1 ,6561.4  ,101.9,98,93.9
BEGIN DESCRIPTION:
Upstream Section of Bridge/Culvert/Weir
END DESCRIPTION:
XS GIS Cut Line= 4
      3064655.77      13933029.8      3063254.12     13931688.33
      3062952.82     13931485.46      3060056.81     13929607.92
#Sta/Elev= 30
  2898.9  129.89  2948.9  130.92  3018.9  128.49  3338.9   127.3  3378.9  129.18
  3578.9  129.36  3618.9  127.95  3928.9  129.31  4128.9  127.73  4168.9  129.47
  4238.9   128.8  4244.9  130.69  4364.9  128.79  4908.1  127.89  4944.7  118.99
    4999  110.17    5010  110.61  5012.4  113.14  5013.6  116.93  5060.9  127.31
  5618.3  126.99  5638.3  128.49  5668.3  126.49  5678.3  128.49  5748.3  127.59
  5938.3  129.49  6028.3  129.69  6055.9  127.87  7665.9  130.96  8657.4  130.75
#Mann= 4 ,-1 , 0
  2898.9      .1       0  4908.1     .04       0  5060.9     .08       0
  5938.3      .1       0
#XS Ineff= 2 , 0
       0  4898.1  127.38  5070.9       0  127.54
Permanent Ineff=
       F       F
Bank Sta=4908.1,5060.9
XS Rating Curve= 0
Exp/Cntr=.5,.3

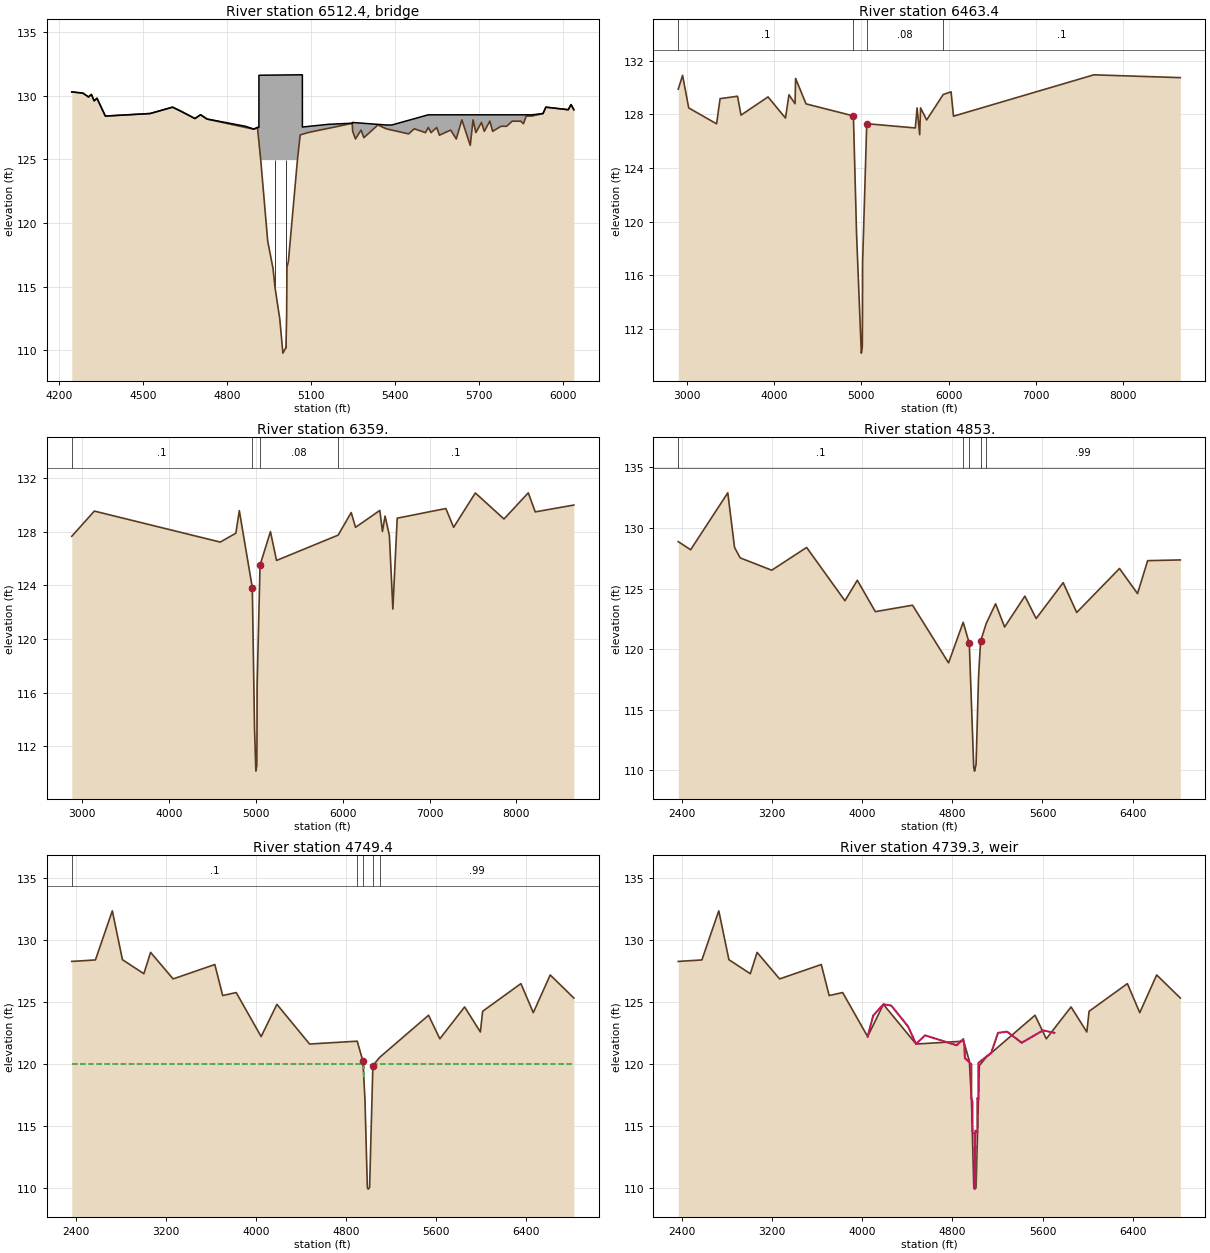
Type RM Length L Ch R = 3 ,6512.4  ,,,
BEGIN DESCRIPTION:
LOUETTA
Structure ID: K133-00-00-S4
Crossing pipeline right in front of bridge not seen modeled 11/11/2 VRR
END DESCRIPTION:
Bridge Culvert--1,0,-1,-1, 0
Deck Dist Width WeirC Skew NumUp NumDn MinLoCord MaxHiCord MaxSubmerge Is_Ogee
10,70,2.6,0, 60, 60, , , .95, 0, 1,1,,
  4244.9  4284.9  4304.9  4314.9  4324.9  4334.9  4364.9  4524.9  4604.9  4684.9
  4704.9  4728.2  4865.2  4895.5  4908.2 4913.29  4913.4 4919.95 5050.86  5060.9
  5068.6 5068.71  5160.3  5246.7  5248.3  5258.3  5278.3  5288.3  5338.3  5368.2
  5388.2  5448.3  5468.3  5508.3  5518.3  5528.3  5548.3  5558.3  5598.3  5618.3
  5638.3  5668.3  5678.3  5688.3  5708.3  5718.3  5738.3  5748.3  5778.3  5798.3
  5818.3  5848.3  5858.3  5868.3  5888.3  5928.3  5938.3  6018.3  6028.3  6038.3
   130.3   130.2   129.9   130.1   129.6   129.8   128.4   128.6   129.1  128.21
  128.51  128.17   127.6  127.38  127.51   127.5   131.6  131.61  131.64  131.64
  131.64  127.54  127.75  127.84   127.9  127.88  127.85  127.83  127.75   127.7
   127.7  128.07  128.19  128.44   128.5   128.5   128.5   128.5   128.5   128.5
   128.5   128.5   128.5   128.5   128.5   128.5   128.5   128.5   128.5   128.5
   128.5   128.5   128.5   128.5   128.5   128.6   129.1   128.9   129.3   128.9
   130.3   130.2   129.9   130.1   129.6   129.8   128.4   128.6   129.1   128.2
   128.5  128.16  127.51  127.37   127.5  126.39  126.37  124.94  124.94  126.92
  126.97  126.97  127.43  127.83   127.2   126.6   127.3   126.7   127.7   127.4
   127.3     127   127.4   127.1   127.5   127.1   127.5   126.9   127.3   126.6
   128.1   126.1   128.1   127.1   127.9   127.2     128   127.2   127.6   127.6
     128     128   127.8   128.4   128.4   128.6   129.1   128.9   129.3   128.9
  4244.9  4284.9  4304.9  4314.9  4324.9  4334.9  4364.9  4524.9  4604.9  4684.9
  4704.9  4728.2  4865.2  4895.5  4908.2 4913.29  4913.4 4919.95 5050.86  5060.9
  5068.6 5068.71  5160.3  5246.7  5248.3  5258.3  5278.3  5288.3  5338.3  5368.2
  5388.2  5448.3  5468.3  5508.3  5518.3  5528.3  5548.3  5558.3  5598.3  5618.3
  5638.3  5668.3  5678.3  5688.3  5708.3  5718.3  5738.3  5748.3  5778.3  5798.3
  5818.3  5848.3  5858.3  5868.3  5888.3  5928.3  5938.3  6018.3  6028.3  6038.3
   130.3   130.2   129.9   130.1   129.6   129.8   128.4   128.6   129.1  128.21
  128.51  128.17   127.6  127.38  127.51   127.5   131.6  131.61  131.64  131.64
  131.64  127.54  127.75  127.84   127.9  127.88  127.85  127.83  127.75   127.7
   127.7  128.07  128.19  128.44   128.5   128.5   128.5   128.5   128.5   128.5
   128.5   128.5   128.5   128.5   128.5   128.5   128.5   128.5   128.5   128.5
   128.5   128.5   128.5   128.5   128.5   128.6   129.1   128.9   129.3   128.9
   130.3   130.2   129.9   130.1   129.6   129.8   128.4   128.6   129.1   128.2
   128.5  128.16  127.51  127.37   127.5  126.39  126.37  124.94  124.94  126.92
  126.97  126.97  127.43  127.83   127.2   126.6   127.3   126.7   127.7   127.4
   127.3     127   127.4   127.1   127.5   127.1   127.5   126.9   127.3   126.6
   128.1   126.1   128.1   127.1   127.9   127.2     128   127.2   127.6   127.6
     128     128   127.8   128.4   128.4   128.6   129.1   128.9   129.3   128.9
Pier Skew, UpSta & Num, DnSta & Num=  ,4970.9, 2 ,4970.9, 2 , 0 , 0 , 0 ,,
     1.3     1.3
  113.85  125.94
     1.3     1.3
  114.24  126.33
Pier Skew, UpSta & Num, DnSta & Num=  ,5010, 2 ,5010, 2 , 0 , 0 , 0 ,,
     1.3     1.3
  109.19  125.94
     1.3     1.3
  109.58  126.33
BR Coef= 1 , 1 , 1 ,1.25, 0 ,,,.8,0,2,0,
WSPro=,,,, 1 ,,,, 0 ,,,, 0 ,,,,-1 ,-1 ,-1 , 0 , 0 , 0 , 0 , 0
BR U #Sta/Elev= 95
  4244.9   130.3  4284.9   130.2  4304.9   129.9  4314.9   130.1  4324.9   129.6
  4334.9   129.8  4364.9   128.4  4524.9   128.6  4604.9   129.1  4634.9   128.8
  4648.2  128.64  4684.9   128.2  4704.9   128.5  4728.2  128.16  4768.9  127.97
  4814.1  127.75  4865.2  127.51  4895.5  127.37  4908.1   127.5  4908.2   127.5
 4913.29  126.39  4913.4  126.37 4913.51  126.34 4914.21  126.19  4914.3  126.17
  4914.4  126.15 4919.95  124.94  4943.2  118.98  4944.7   118.6  4963.9  116.41
  4970.9  114.95  4982.9  113.18  4985.5   112.8  4987.7  112.52    4999  109.78
    5010  110.22  5012.4  112.75  5013.6  116.54  5018.7  116.98  5023.7  118.22
 5050.86  124.94  5054.6  125.68 5054.69   125.7  5054.8  125.72  5060.9  126.92
 5068.49  126.97  5068.6  126.97 5068.71  126.97  5088.5   127.1  5117.9  127.24
  5160.3  127.43  5203.8  127.63  5246.1  127.83  5246.7  127.83  5248.2  127.24
  5248.3   127.2  5258.3   126.6    5262  126.73  5278.3   127.3  5288.3   126.7
  5338.3   127.7  5368.2   127.4  5368.3   127.4  5388.2   127.3  5448.3     127
  5468.3   127.4  5508.3   127.1  5518.2   127.5  5518.3   127.5  5528.3   127.1
  5548.3   127.5  5558.3   126.9  5598.3   127.3  5618.3   126.6  5638.3   128.1
  5668.3   126.1  5678.3   128.1  5688.3   127.1  5708.3   127.9  5718.3   127.2
  5738.3     128  5748.3   127.2  5778.3   127.6  5798.3   127.6  5818.3     128
  5848.3     128  5858.3   127.8  5868.3   128.4  5888.3   128.4  5928.2   128.6
  5928.3   128.6  5938.3   129.1  6018.3   128.9  6028.3   129.3  6038.3   128.9
BR U #Mann= 6
  4244.9      .1  4908.1    .015  4963.9     .04  5013.6    .015  5060.9     .08
  5938.3      .1
BR U Banks=4908.1,5060.9
BR D #Sta/Elev= 95
  4244.9  130.69  4284.9  130.59  4304.9  130.29  4314.9  130.49  4324.9  129.99
  4334.9  130.19  4364.9  128.79  4524.9  128.99  4604.9  129.49  4634.9  129.19
  4648.2  129.03  4684.9  128.59  4704.9  128.89  4728.2  128.55  4768.9  128.36
  4814.1  128.14  4865.2   127.9  4895.5  127.76  4908.1  127.89  4908.2  127.89
 4913.29  126.78  4913.4  126.76 4913.51  126.73 4914.21  126.58  4914.3  126.56
  4914.4  126.54 4919.95  125.33  4943.2  119.37  4944.7  118.99  4963.9   116.8
  4970.9  115.34  4982.9  113.57  4985.5  113.19  4987.7  112.91    4999  110.17
    5010  110.61  5012.4  113.14  5013.6  116.93  5018.7  117.37  5023.7  118.61
 5050.86  125.33  5054.6  126.07 5054.69  126.09  5054.8  126.11  5060.9  127.31
 5068.49  127.36  5068.6  127.36 5068.71  127.36  5088.5  127.49  5117.9  127.63
  5160.3  127.82  5203.8  128.02  5246.1  128.22  5246.7  128.22  5248.2  127.63
  5248.3  127.59  5258.3  126.99    5262  127.12  5278.3  127.69  5288.3  127.09
  5338.3  128.09  5368.2  127.79  5368.3  127.79  5388.2  127.69  5448.3  127.39
  5468.3  127.79  5508.3  127.49  5518.2  127.89  5518.3  127.89  5528.3  127.49
  5548.3  127.89  5558.3  127.29  5598.3  127.69  5618.3  126.99  5638.3  128.49
  5668.3  126.49  5678.3  128.49  5688.3  127.49  5708.3  128.29  5718.3  127.59
  5738.3  128.39  5748.3  127.59  5778.3  127.99  5798.3  127.99  5818.3  128.39
  5848.3  128.39  5858.3  128.19  5868.3  128.79  5888.3  128.79  5928.2  128.99
  5928.3  128.99  5938.3  129.49  6018.3  129.29  6028.3  129.69  6038.3  129.29
BR D #Mann= 6
  4244.9      .1  4908.1    .015  4963.9     .04  5013.6    .015  5060.9     .08
  5938.3      .1
BR D Banks=4908.1,5060.9
BC Design=,, 0 ,, 0 ,,,,,,

Type RM Length L Ch R = 1 ,6463.4  ,141.7,104.4,70.7
BEGIN DESCRIPTION:
Downstream Section of Bridge/Culvert/Weir
END DESCRIPTION:
XS GIS Cut Line= 4
      3064686.73     13932944.31      3063283.85     13931601.66
      3062980.98     13931397.73      3060084.82      13929520.1
#Sta/Elev= 30
  2898.9  129.89  2948.9  130.92  3018.9  128.49  3338.9   127.3  3378.9  129.18
  3578.9  129.36  3618.9  127.95  3928.9  129.31  4128.9  127.73  4168.9  129.47
  4238.9   128.8  4244.9  130.69  4364.9  128.79  4908.1  127.89  4944.7  118.99
    4999  110.17    5010  110.61  5012.4  113.14  5013.6  116.93  5060.9  127.31
  5618.3  126.99  5638.3  128.49  5668.3  126.49  5678.3  128.49  5748.3  127.59
  5938.3  129.49  6028.3  129.69  6055.9  127.87  7665.9  130.96  8657.4  130.75
#Mann= 4 ,-1 , 0
  2898.9      .1       0  4908.1     .04       0  5060.9     .08       0
  5938.3      .1       0
#XS Ineff= 2 , 0
       0    4909  124.95    5060       0  124.95
Permanent Ineff=
       F       F
Bank Sta=4908.1,5060.9
XS Rating Curve= 0
Exp/Cntr=.5,.3

Type RM Length L Ch R = 1 ,6359.   ,1424.2,1506,1560.4
BEGIN DESCRIPTION:
K133-00-00-S4_LOUETTA-DS - XS 1
END DESCRIPTION:
XS GIS Cut Line= 4
      3064680.09      13932846.8      3063182.64     13931403.52
      3063104.92     13931417.03      3060078.18     13929422.64
#Sta/Elev= 30
  2878.2  127.65  3138.2  129.53  4588.2  127.22  4768.2  127.88  4808.2  129.56
    4958  123.82 4983.26  113.38 4998.88  110.15 5009.67  110.57 5012.03  112.95
  5013.2  116.51  5046.9   125.5  5166.9     128  5236.9  125.85  5946.9  127.74
  6096.9  129.42  6146.9  128.32  6426.9  129.58  6456.9  128.01  6486.9  129.16
  6536.9  127.71  6576.9  122.23  6626.9     129  7186.9  129.72  7276.9  128.32
  7526.9  130.88  7856.9  128.94  8136.9  130.89  8216.9  129.47  8661.6  129.98
#Mann= 4 ,-1 , 0
  2878.2      .1       0    4958     .04       0  5046.9     .08       0
  5946.9      .1       0
Bank Sta=4958,5046.9
XS Rating Curve= 0
Exp/Cntr=.3,.1

Type RM Length L Ch R = 1 ,4853.   ,105,103.6,103.1
BEGIN DESCRIPTION:
K133-00-00-S3-1_WEIR-US - XS 4
END DESCRIPTION:
XS GIS Cut Line= 4
      3064823.51      13932730.3      3063931.79     13930347.55
      3063910.85     13930155.14      3062611.76     13929028.05
#Sta/Elev= 30
  2366.2  128.87  2476.2   128.2  2806.2   132.9  2866.2  128.39  2916.2  127.53
  3196.2  126.51  3506.2  128.39  3846.2  123.99  3956.2  125.68  4116.2  123.09
  4446.2  123.62  4766.2  118.86  4896.2  122.21  4950.4  120.47 4989.81  110.21
 4997.21  109.92 5010.48  110.48 5032.39  117.69  5050.4  120.63  5100.4  122.11
  5183.9  123.74  5263.9  121.82  5443.9  124.37  5543.9  122.52  5783.9  125.48
  5903.9  123.02  6283.9  126.65  6443.9  124.58  6533.9   127.3  6823.8  127.36
#Mann= 5 ,-1 , 0
  2366.2      .1       0  4896.2    .045       0  4950.4     .04       0
  5050.4    .045       0  5100.4     .99       0
#XS Ineff= 2 , 0
       0  4896.2  122.21               0
Permanent Ineff=
       F       F
Bank Sta=4950.4,5050.4
XS Rating Curve= 0
Exp/Cntr=.7,.5

Type RM Length L Ch R = 1 ,4749.4  ,21,20.2,20
BEGIN DESCRIPTION:
Upstream Section of Bridge/Culvert/Weir
END DESCRIPTION:
XS GIS Cut Line= 4
       3064925.4     13932714.83      3064033.68     13930332.05
      3064012.73     13930139.64     3062713.647    13929012.541
#Sta/Elev= 30
  2365.8  128.26  2575.8  128.38  2725.8  132.34  2815.8   128.4  3005.8  127.27
  3065.8  128.99  3265.8  126.85  3635.8  128.01  3705.8  125.51  3825.8  125.75
  4047.2   122.2  4187.2   124.8  4477.2   121.6    4900  121.83  4950.7  120.22
    4969  117.11  4990.1  110.02  4997.1   109.9    5010  110.04  5039.2  119.86
    5100  120.53  5533.5  123.92  5633.5  122.02  5853.5  124.59  5993.5  122.57
  6013.5  124.24  6353.5  126.47  6463.5  124.13  6613.5  127.17  6823.4  125.31
#Mann= 5 ,-1 , 0
  2365.8      .1       0    4900    .045       0  4950.7     .04       0
  5039.2    .045       0    5100     .99       0
#XS Ineff= 2 , 0
       0 4958.74     120 5041.26       0     120
Permanent Ineff=
       F       F
Bank Sta=4950.7,5039.2
XS Rating Curve= 0
Exp/Cntr=.7,.5

Type RM Length L Ch R = 5 ,4739.3  ,,,
BEGIN DESCRIPTION:
WEIR 170' US OF HERTS RD
Structure ID: K133-00-00-S3-1
END DESCRIPTION:
IW Pilot Flow=0
#Inline Weir SE= 30
  4047.2   122.2  4097.2   123.9  4187.2   124.8  4257.2   124.7  4407.2     123
  4477.2   121.6  4557.2   122.3  4837.2   121.5  4897.2     122  4907.2   121.4
  4909.9  120.47  4968.7  119.97  4968.8  117.17  4978.2  116.94  4978.3   114.5
  4996.8  114.35  4997.1  109.93    5003  109.97  5003.3  114.62  5021.8  114.47
  5021.9  117.24  5030.9   117.1  5031.1  117.17  5031.3  120.08  5144.9   120.9
  5204.9   122.5  5284.9   122.6  5414.9   121.7  5604.9   122.7  5704.9   122.5
IW Dist,WD,Coef,Skew,MaxSub,Min_El,Is_Ogee,SpillHt,DesHd
10,1,2.6,0,.95,, 0 ,,,0,0,

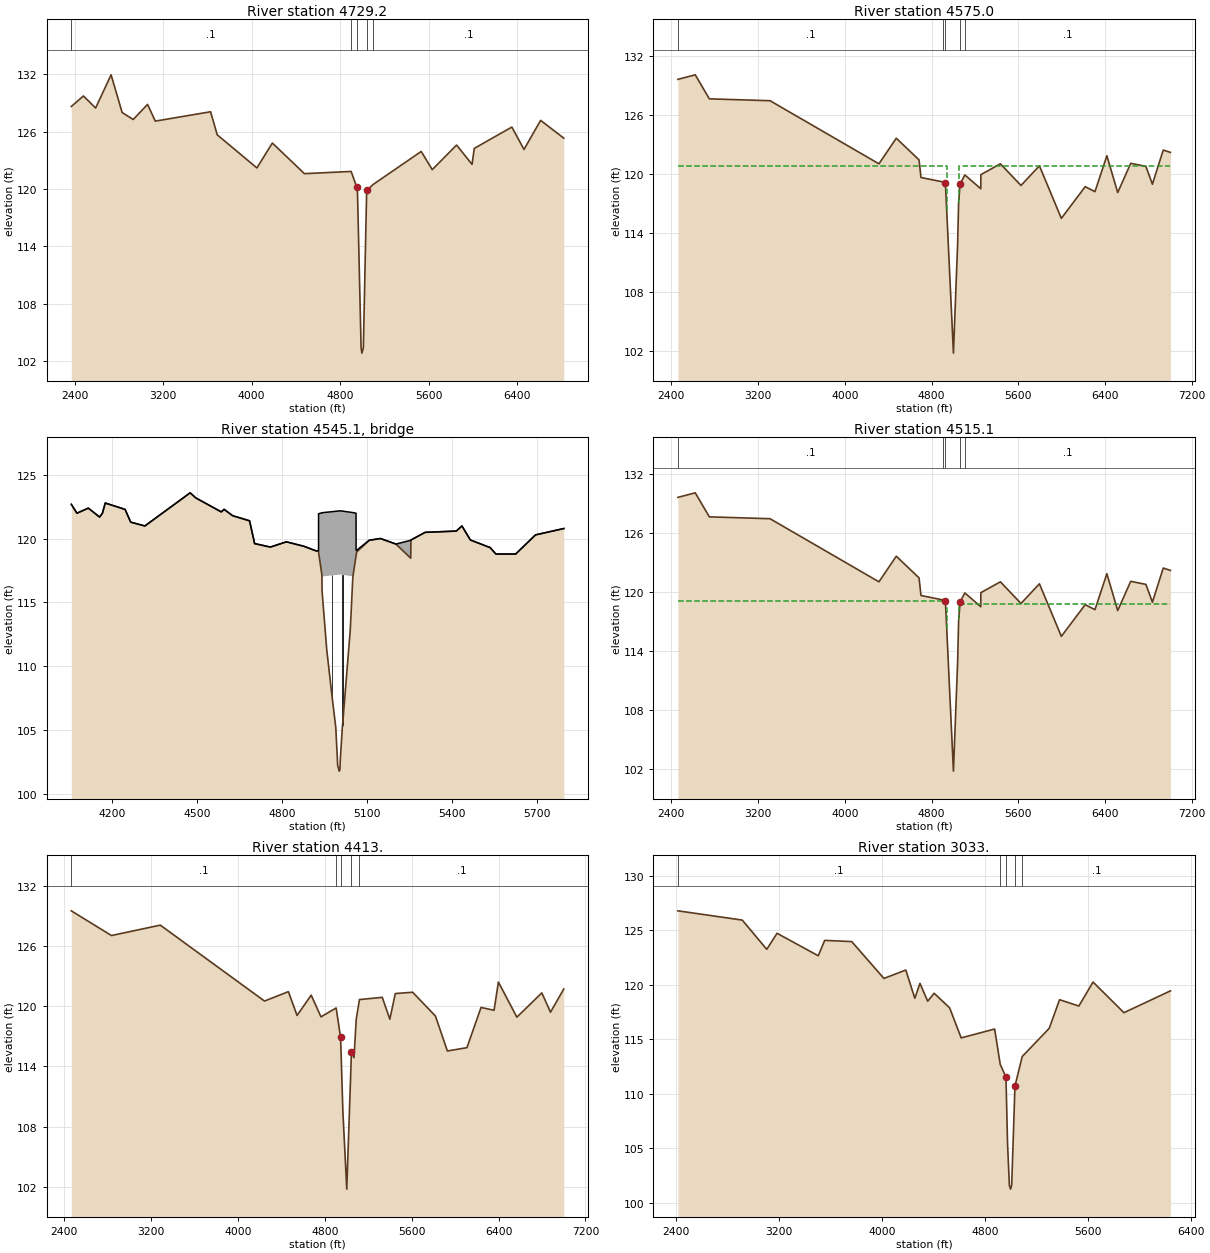
Type RM Length L Ch R = 1 ,4729.2  ,155,154.2,152.7
BEGIN DESCRIPTION:
Cross Section FIELD_DS
Located At: WEIR 170' US OF HERTS RD
END DESCRIPTION:
XS GIS Cut Line= 4
      3064944.13     13932707.82      3064053.29     13930327.39
       3064032.4      13930135.5     3062729.957    13928989.707
#Sta/Elev= 30
  2368.3  128.62  2478.3  129.72  2588.3  128.46  2728.3  131.93  2828.3  127.99
  2928.3  127.26  3058.3  128.84  3128.3  127.09  3628.3  128.07  3688.3  125.66
  4047.2   122.2  4187.2   124.8  4477.2   121.6    4900  121.83  4949.6  120.22
  4957.5  119.54  4989.8   103.4    4997  102.84  5010.3   103.4  5040.2  119.86
    5100  120.48  5533.5  123.92  5633.5  122.02  5853.5  124.59  5993.5  122.57
  6013.5  124.24  6353.5  126.47  6463.5  124.13  6613.5  127.17  6823.4  125.31
#Mann= 5 ,-1 , 0
  2368.3      .1       0    4900    .045       0  4949.6    .045       0
  5040.2    .045       0    5100      .1       0
Bank Sta=4949.6,5040.2
XS Rating Curve= 0
Exp/Cntr=.7,.5

Type RM Length L Ch R = 1 ,4575.0  ,61,59.9,59
BEGIN DESCRIPTION:
Upstream Section of Bridge/Culvert/Weir
END DESCRIPTION:
XS GIS Cut Line= 4
      3065022.04     13932619.21      3064214.39     13930375.92
      3064164.82     13929962.77       3063683.5     13928285.87
#Sta/Elev= 30
  2459.9  129.59  2619.9  130.05  2749.9  127.61  3309.9  127.42  4314.5  121.01
  4474.5  123.61  4684.5  121.41  4702.4  119.62    4905  119.17  4927.8  119.03
  5001.7  101.78  5040.2  112.81  5049.4     117  5062.8  118.96  5107.1  119.88
  5254.1  118.48  5254.8  119.91  5434.9  121.01  5624.9  118.81  5794.9  120.81
  5997.3  115.47  6217.3  118.69  6307.3  118.18  6417.3  121.83  6517.3  118.09
  6637.3  121.06  6777.3  120.75  6837.3  118.94  6937.3  122.41  7003.5  122.17
#Mann= 5 ,-1 , 0
  2459.9      .1       0    4905    .045       0  4927.8     .04       0
  5062.8    .045       0  5107.1      .1       0
#XS Ineff= 2 , 0
       0 4940.15  120.76  5049.5       0  120.76
Permanent Ineff=
       F       F
Bank Sta=4927.8,5062.8
XS Rating Curve= 0
Exp/Cntr=.5,.3

Type RM Length L Ch R = 3 ,4545.1  ,,,
BEGIN DESCRIPTION:
HERTS RD
Structure ID: K133-00-00-S3
END DESCRIPTION:
Bridge Culvert--1,0,-1,-1, 0
Deck Dist Width WeirC Skew NumUp NumDn MinLoCord MaxHiCord MaxSubmerge Is_Ogee
10,38,2.6,0, 45, 45, , , .95, 0, 1,1,,
  4054.5  4074.5  4114.5  4154.5  4164.5  4174.5  4244.5  4264.5  4314.5  4474.5
  4494.5  4584.5  4594.5  4624.5  4684.5  4702.4  4758.1  4814.4  4876.7  4919.7
  4927.8 4928.19  4928.3  4940.2 4940.31  5005.2 5049.82  5060.8 5060.91  5062.8
  5107.1  5146.9  5202.1  5254.1  5254.5  5254.8  5304.9  5414.9  5434.9  5464.9
  5534.9  5554.9  5624.9  5694.9  5794.9
   122.7     122   122.4   121.7     122   122.8   122.3   121.3     121   123.6
   123.2  122.11  122.31  121.81  121.41  119.62  119.35  119.76  119.41  119.05
  119.06  119.06  121.96  122.03  122.04  122.19  122.05     122   119.1  119.09
  119.88  120.02  119.58  119.88  119.89   119.9   120.5   120.6     121   119.9
   119.3   118.8   118.8   120.3   120.8
   122.7     122   122.4   121.7     122   122.8   122.3   121.3     121   123.6
   123.2   122.1   122.3   121.8   121.4  119.61  119.34  119.75   119.4  119.04
  119.02  118.96  118.94  117.13  117.04  117.19  117.05  118.66  118.67  118.95
  119.87  120.01  119.57  118.47  119.57   119.9   120.5   120.6     121   119.9
   119.3   118.8   118.8   120.3   120.8
  4054.5  4074.5  4114.5  4154.5  4164.5  4174.5  4244.5  4264.5  4314.5  4474.5
  4495.2  4584.5  4594.5  4624.5  4684.5  4702.4  4758.1  4814.4  4876.7  4919.7
  4927.8 4928.19  4928.3  4940.2 4940.31  5005.2 5049.82  5060.8 5060.91  5062.8
  5107.1  5146.9  5202.1  5254.1  5254.5  5254.8  5304.9  5414.9  5434.9  5464.9
  5534.9  5554.9  5624.9  5694.9  5794.9
  122.71  122.01  122.41  121.71  122.01  122.81  122.31  121.31  121.01  123.61
   123.2  122.11  122.31  121.81  121.41  119.62  119.35  119.76  119.41  119.05
  119.06  119.06  121.96  122.03  122.04  122.19  122.05     122   119.1  119.09
  119.88  120.02  119.58  119.88  119.89  119.91  120.51  120.61  121.01  119.91
  119.31  118.81  118.81  120.31  120.81
  122.71  122.01  122.41  121.71  122.01  122.81  122.31  121.31  121.01  123.61
   123.2  122.11  122.31  121.81  121.41  119.62  119.35  119.76  119.41  119.05
  119.03  118.97  118.95  117.14  117.05   117.2  117.06  118.67  118.68  118.96
  119.88  120.02  119.58  118.48  119.58  119.91  120.51  120.61  121.01  119.91
  119.31  118.81  118.81  120.31  120.81
Pier Skew, UpSta & Num, DnSta & Num=  ,4976.4, 2 ,4976.4, 2 , 0 , 0 , 0 ,,
     1.3     1.3
  106.43  118.17
     1.3     1.3
  106.44  118.18
Pier Skew, UpSta & Num, DnSta & Num=  ,5013.1, 2 ,5013.1, 2 , 0 , 0 , 0 ,,
     1.3     1.3
  104.26  118.19
     1.3     1.3
  104.27   118.2
BR Coef= 1 , 1 , 1 ,1.25, 0 ,,,.8,0,2,0,
WSPro=,,,, 1 ,,,, 0 ,,,, 0 ,,,,-1 ,-1 ,-1 , 0 , 0 , 0 , 0 , 0
BR U #Sta/Elev= 87
  4054.5   122.7  4064.7  122.34  4074.5     122  4114.5   122.4  4154.5   121.7
  4164.5     122  4174.5   122.8  4244.5   122.3  4264.5   121.3  4314.5     121
  4474.5   123.6  4494.5   123.2  4495.2  123.19  4515.2  122.95  4575.2  122.21
  4584.5   122.1  4585.2  122.11  4594.5   122.3  4595.2  122.29  4624.5   121.8
  4635.2  121.73  4675.2  121.46  4684.5   121.4  4685.2  121.33  4702.4  119.61
  4705.2   119.6  4717.1  119.54  4758.1  119.34  4769.4  119.42  4814.4  119.75
  4822.1  119.71  4876.7   119.4  4877.9  119.39    4905  119.16  4919.7  119.04
  4925.6  119.03  4927.8  119.02 4928.19  118.96  4928.3  118.94 4928.41  118.93
  4938.9  117.33 4939.01  117.31  4939.1   117.3  4940.2  117.13 4940.31  117.04
  4940.6  115.92  4957.2  111.29    4976  107.63  4976.4  107.55  4989.1  105.21
  4994.8  102.72  4995.8  102.21  5001.7  101.77  5003.7  101.88  5005.2  102.71
  5012.4  105.25    5013  105.35  5013.1  105.38  5040.2   112.8  5049.4  116.99
 5049.82  117.05 5049.99  117.07  5050.1  117.09  5050.2  117.11 5060.69  118.64
  5060.8  118.66 5060.91  118.67  5062.8  118.95  5107.1  119.87  5109.1  119.88
  5146.8  120.01  5146.9  120.01  5201.6  119.58  5202.1  119.57  5254.1  118.47
  5254.5  119.57  5254.8   119.9 5254.91   119.9  5304.9   120.5  5414.9   120.6
  5434.9     121  5464.9   119.9  5534.9   119.3  5554.9   118.8  5624.9   118.8
  5694.9   120.3  5794.9   120.8
BR U #Mann= 5
  4054.5      .1    4905    .045  4927.8     .04  5062.8    .045  5107.1      .1
BR U Banks=4927.8,5062.8
BR D #Sta/Elev= 87
  4054.5  122.71  4064.7  122.35  4074.5  122.01  4114.5  122.41  4154.5  121.71
  4164.5  122.01  4174.5  122.81  4244.5  122.31  4264.5  121.31  4314.5  121.01
  4474.5  123.61  4494.5  123.21  4495.2   123.2  4515.2  122.96  4575.2  122.22
  4584.5  122.11  4585.2  122.12  4594.5  122.31  4595.2   122.3  4624.5  121.81
  4635.2  121.74  4675.2  121.47  4684.5  121.41  4685.2  121.34  4702.4  119.62
  4705.2  119.61  4717.1  119.55  4758.1  119.35  4769.4  119.43  4814.4  119.76
  4822.1  119.72  4876.7  119.41  4877.9   119.4    4905  119.17  4919.7  119.05
  4925.6  119.04  4927.8  119.03 4928.19  118.97  4928.3  118.95 4928.41  118.94
  4938.9  117.34 4939.01  117.32  4939.1  117.31  4940.2  117.14 4940.31  117.05
  4940.6  115.93  4957.2   111.3    4976  107.64  4976.4  107.56  4989.1  105.22
  4994.8  102.73  4995.8  102.22  5001.7  101.78  5003.7  101.89  5005.2  102.72
  5012.4  105.26    5013  105.36  5013.1  105.39  5040.2  112.81  5049.4     117
 5049.82  117.06 5049.99  117.08  5050.1   117.1  5050.2  117.12 5060.69  118.65
  5060.8  118.67 5060.91  118.68  5062.8  118.96  5107.1  119.88  5109.1  119.89
  5146.8  120.02  5146.9  120.02  5201.6  119.59  5202.1  119.58  5254.1  118.48
  5254.5  119.58  5254.8  119.91 5254.91  119.91  5304.9  120.51  5414.9  120.61
  5434.9  121.01  5464.9  119.91  5534.9  119.31  5554.9  118.81  5624.9  118.81
  5694.9  120.31  5794.9  120.81
BR D #Mann= 5
  4054.5      .1    4905    .045  4927.8     .04  5062.8    .045  5107.1      .1
BR D Banks=4927.8,5062.8
BC Design=,, 0 ,, 0 ,,,,,,

Type RM Length L Ch R = 1 ,4515.1  ,108.8,102.1,96.3
BEGIN DESCRIPTION:
Downstream Section of Bridge/Culvert/Weir
END DESCRIPTION:
XS GIS Cut Line= 4
      3065080.74     13932611.81      3064273.86     13930370.66
      3064224.37     13929958.17      3063742.61     13928279.73
#Sta/Elev= 30
  2459.9  129.59  2619.9  130.05  2749.9  127.61  3309.9  127.42  4314.5  121.01
  4474.5  123.61  4684.5  121.41  4702.4  119.62    4905  119.17  4927.8  119.03
  5001.7  101.78  5040.2  112.81  5049.4     117  5062.8  118.96  5107.1  119.88
  5254.1  118.48  5254.8  119.91  5434.9  121.01  5624.9  118.81  5794.9  120.81
  5997.3  115.47  6217.3  118.69  6307.3  118.18  6417.3  121.83  6517.3  118.09
  6637.3  121.06  6777.3  120.75  6837.3  118.94  6937.3  122.41  7003.5  122.17
#Mann= 5 ,-1 , 0
  2459.9      .1       0    4905    .045       0  4927.8     .04       0
  5062.8    .045       0  5107.1      .1       0
#XS Ineff= 2 , 0
       0 4940.15  119.05 5050.11       0   118.8
Permanent Ineff=
       F       F
Bank Sta=4927.8,5062.8
XS Rating Curve= 0
Exp/Cntr=.5,.3

Type RM Length L Ch R = 1 ,4413.   ,1394.3,1380,1352.9
BEGIN DESCRIPTION:
K133-00-00-S3_HERTS RD - DS - XS 1
END DESCRIPTION:
XS GIS Cut Line= 4
      3065180.41      13932587.4      3064369.03     13930242.94
      3064341.74     13930142.87      3063842.28     13928255.37
#Sta/Elev= 30
  2463.8  129.56  2833.8  127.09  3283.8  128.13  4243.8  120.54  4463.8  121.48
  4543.8   119.1  4673.8  121.13  4763.8  118.96  4903.8  119.85  4944.7   116.9
 4965.96  109.45  5001.6  101.74  5044.7  115.46  5068.5  114.89  5088.5   118.7
  5118.5  120.69  5328.5  120.91  5398.5  118.73  5448.5  121.29  5608.5  121.42
  5818.5  119.04  5928.5  115.55  6108.5  115.88  6238.5   119.9  6358.5  119.62
  6398.5  122.44  6568.5  118.93  6798.5  121.36  6878.5  119.43  7000.9  121.75
#Mann= 5 ,-1 , 0
  2463.8      .1       0  4903.8    .045       0  4944.7     .04       0
  5044.7    .045       0  5118.5      .1       0
Bank Sta=4944.7,5044.7
XS Rating Curve= 0
Exp/Cntr=.3,.1

Type RM Length L Ch R = 1 ,3033.   ,87.6,104.2,133.8
BEGIN DESCRIPTION:
K133-00-00-S2-1_WEIR-US - XS 4
END DESCRIPTION:
XS GIS Cut Line= 4
      3065741.17       13931574.      3065176.65     13929099.85
      3065098.08     13929028.33      3064413.05     13928066.26
#Sta/Elev= 30
  2416.7  126.77  2916.7  125.92  3106.7  123.24  3186.7  124.71  3506.7  122.65
  3556.7  124.06  3766.7  123.95  4016.7  120.57  4186.7  121.34  4256.7  118.75
  4296.7  120.12  4356.7  118.48  4406.7  119.21  4526.7  117.88  4616.7  115.12
  4876.7  115.93    4920  112.69  4964.5  111.52 4976.88  105.41 4991.25  101.57
 5000.21  101.25 5008.97  101.62  5034.5  110.71  5090.8  113.41  5300.8     116
  5380.8  118.62  5530.8  118.04  5640.8  120.24  5880.8  117.43  6241.8  119.43
#Mann= 5 ,-1 , 0
  2416.7      .1       0    4920    .045       0  4964.5     .04       0
  5034.5    .045       0  5090.8      .1       0
Bank Sta=4964.5,5034.5
XS Rating Curve= 0
Exp/Cntr=.7,.5