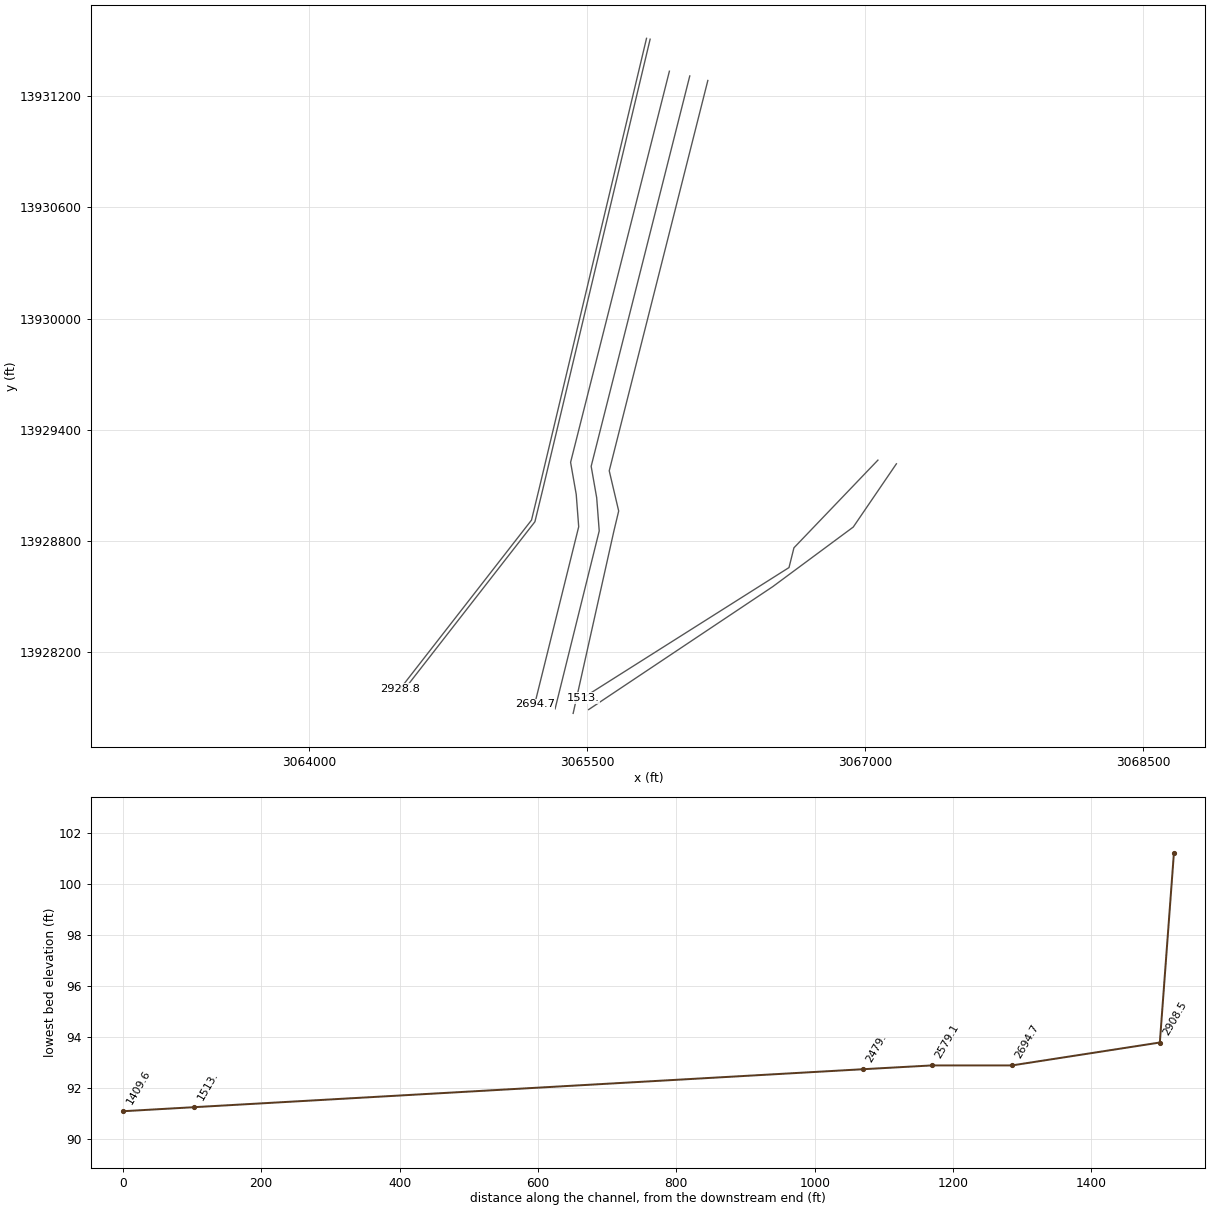
HEC-RAS study K133-00-00.prj: K133-00-00

--- K133-00-00.g01 (geometry) --- (continued)

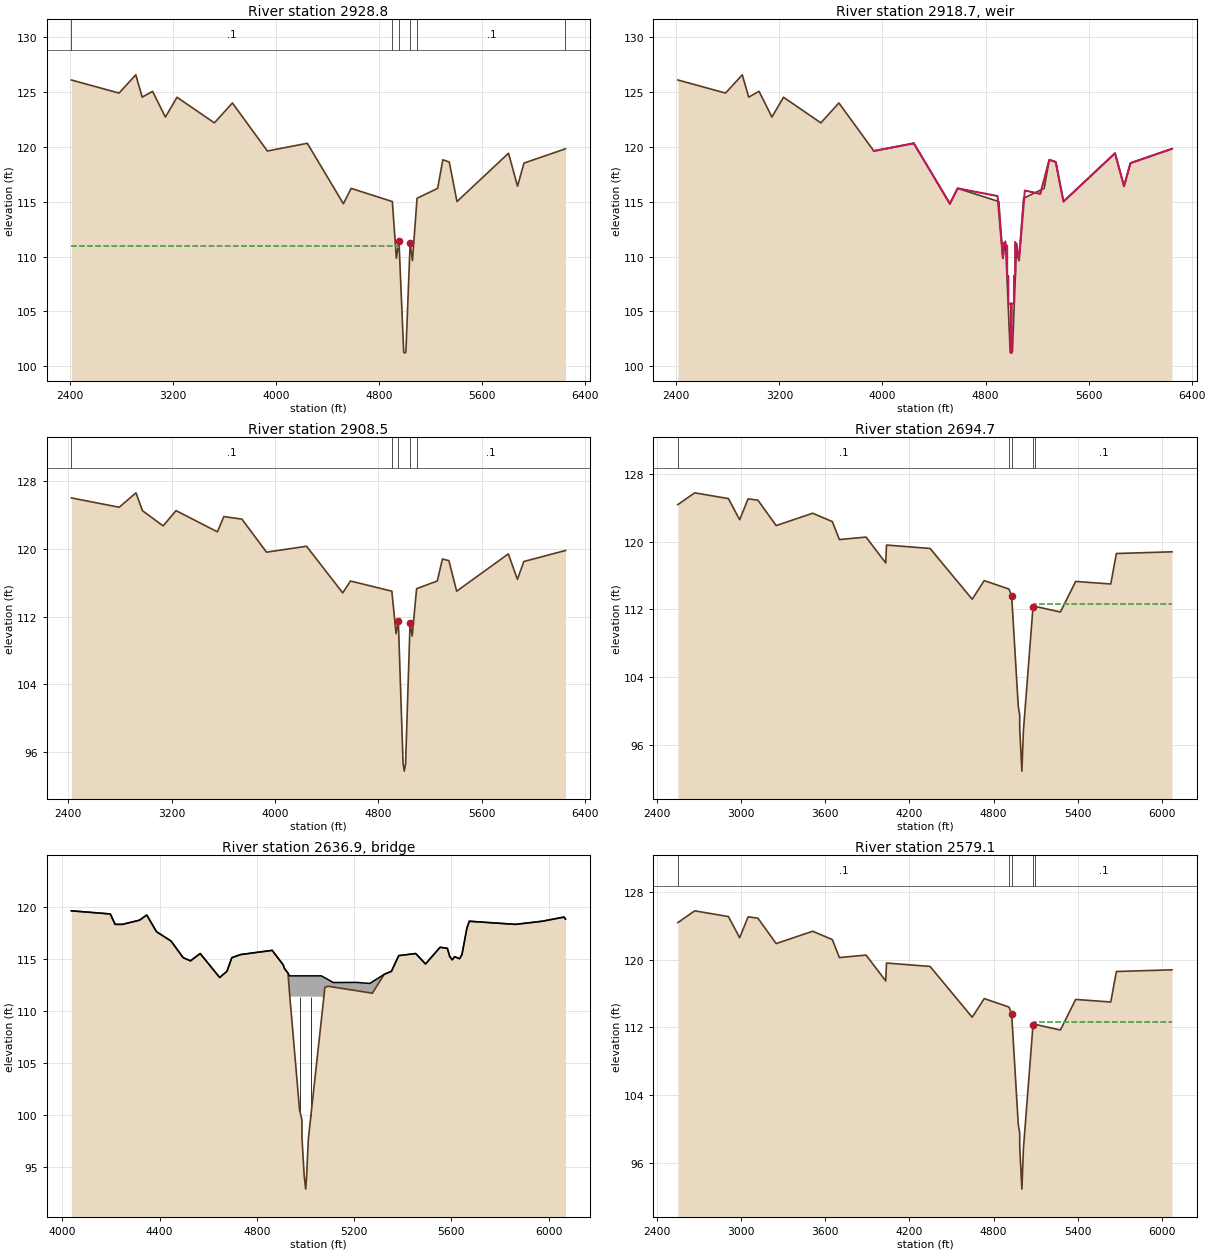
Type RM Length L Ch R = 1 ,2928.8  ,21,20.3,20
BEGIN DESCRIPTION:
Upstream Section of Bridge/Culvert/Weir
END DESCRIPTION:
XS GIS Cut Line= 4
      3065820.91     13931512.06      3065243.86     13929091.91
      3065200.48     13928913.41      3064492.78     13928004.25
#Sta/Elev= 30
    2412  126.06    2782  124.87    2912  126.53    2962   124.5    3042  125.03
    3142  122.69    3232  124.49    3522  122.16    3662  123.97  3933.4   119.6
  4243.4   120.3  4523.4   114.8  4583.4   116.2  4903.4     115  4934.6  109.84
  4954.8   111.4  4991.5   101.3  5000.1  101.21  5008.6  101.33  5041.5   111.2
  5059.5  109.64  5095.1   115.3  5255.1   116.2  5295.1   118.8  5345.1   118.6
  5405.1     115  5805.1   119.4  5875.1   116.4  5925.1   118.5  6247.2   119.8
#Mann= 6 ,-1 , 0
    2412      .1       0  4903.4    .045       0  4954.8     .02       0
  5041.5    .045       0  5095.1      .1       0  6247.2     .99       0
#XS Ineff= 2 , 0
       0  4944.8     111  5051.5       0     110
Permanent Ineff=
       F       F
Bank Sta=4954.8,5041.5
XS Rating Curve= 0
Exp/Cntr=.7,.5

Type RM Length L Ch R = 5 ,2918.7  ,,,
BEGIN DESCRIPTION:
SHEET PILING STR 225' US CHAMPION FOREST
Structure ID: K133-00-00-S2-1
END DESCRIPTION:
IW Pilot Flow=0
#Inline Weir SE= 30
  3933.4   119.6  4243.4   120.3  4523.4   114.8  4583.4   116.2  4893.4   115.5
  4934.6  109.84  4943.3  111.26  4968.4  110.95  4968.5  108.21  4977.5  108.23
  4977.7  105.64  4996.3  105.74  4996.4  101.26  5000.1  101.23  5002.3  101.24
  5002.7  105.72    5021  105.69  5021.3  108.24  5030.2   108.3  5030.6  111.32
  5059.5  109.64  5105.1     116  5225.1   115.7  5295.1   118.8  5345.1   118.6
  5405.1     115  5805.1   119.4  5875.1   116.4  5925.1   118.5  6247.2   119.8
IW Dist,WD,Coef,Skew,MaxSub,Min_El,Is_Ogee,SpillHt,DesHd
10,1,3,0,.95,, 0 ,,,0,0,

Type RM Length L Ch R = 1 ,2908.5  ,196.7,213.8,227.4
BEGIN DESCRIPTION:
Cross Section FIELD_DS
Located At: SHEET PILING STR 225' US CHAMPION FOREST
END DESCRIPTION:
XS GIS Cut Line= 4
      3065840.36     13931507.42       3065263.3     13929087.23
       3065218.9     13928904.51      3064508.57     13927991.96
#Sta/Elev= 30
  2423.4     126  2793.4   124.9  2923.4   126.6  2973.4   124.5  3133.4   122.7
  3233.4   124.5  3553.4     122  3603.4   123.8  3743.4   123.5  3933.4   119.6
  4243.4   120.3  4523.4   114.8  4583.4   116.2  4903.4     115  4936.3  109.99
  4953.7  111.51  4990.3   94.75  4999.4   93.78  5009.8   94.61  5044.6  111.28
    5061  109.71  5095.1   115.3  5255.1   116.2  5295.1   118.8  5345.1   118.6
  5405.1     115  5805.1   119.4  5875.1   116.4  5925.1   118.5  6247.2   119.8
#Mann= 5 ,-1 , 0
  2423.4      .1       0  4903.4    .045       0  4953.7     .04       0
  5044.6    .045       0  5095.1      .1       0
Bank Sta=4953.7,5044.6
XS Rating Curve= 0
Exp/Cntr=.7,.5

Type RM Length L Ch R = 1 ,2694.7  ,112.5,115.6,117
BEGIN DESCRIPTION:
Upstream Section of Bridge/Culvert/Weir
END DESCRIPTION:
XS GIS Cut Line= 5
      3065944.28     13931334.73      3065411.33     13929225.06
       3065441.7     13929051.96      3065455.07     13928877.45
      3065217.72     13927920.67
#Sta/Elev= 30
  2551.7  124.37  2671.7  125.76  2911.7  125.08  2991.7  122.58  3051.7  125.05
  3121.7  124.89  3251.7  121.89  3511.7  123.35  3651.7  122.36  3701.7  120.24
  3891.7  120.53  4031.7  117.48  4037.3  119.59  4347.3  119.19  4647.3  113.19
  4733.2  115.39    4909  114.39  4928.3  113.61  4975.5  100.52  4985.6   99.53
    4986   97.77  5001.2   92.88  5012.1   97.68  5080.2  112.24  5093.4  112.35
  5275.4  111.68    5384  115.29    5634  114.99    5674  118.59  6069.8  118.79
#Mann= 5 ,-1 , 0
  2551.7      .1       0    4909    .045       0  4928.3     .04       0
  5080.2    .045       0  5093.4      .1       0
#XS Ineff= 2 , 0
       0  4918.3   113.2  5090.2       0  112.63
Permanent Ineff=
       F       F
Bank Sta=4928.3,5080.2
XS Rating Curve= 0
Exp/Cntr=.5,.3

Type RM Length L Ch R = 3 ,2636.9  ,,,
BEGIN DESCRIPTION:
CHAMPION FOREST DR BRIDGE
Structure ID: K133-00-00-S2
END DESCRIPTION:
Bridge Culvert--1,0,-1,-1, 0
Deck Dist Width WeirC Skew NumUp NumDn MinLoCord MaxHiCord MaxSubmerge Is_Ogee
10,90,2.6,0, 48, 48, , , .95, 0, 1,1,,
  4037.3  4197.3  4217.3  4247.3  4317.3  4347.3  4387.3  4447.3  4497.3  4527.3
  4567.3  4647.3  4677.3  4697.3  4733.2  4863.2    4909  4913.4  4928.3 4934.41
    4936  5065.7 5072.29  5072.4  5080.2  5093.4  5114.6  5211.3  5264.7  5275.4
  5323.9    5354    5384    5454    5494    5554    5584    5594    5604    5614
    5634    5644    5664    5674    5864    5974    6064  6069.8
   119.6   119.3   118.3   118.3   118.7   119.2   117.6   116.7   115.1   114.8
   115.5   113.2   113.8   115.1   115.4  115.81  114.41  114.08  113.63  113.36
  113.36  113.36  113.27  113.27  113.17     113  112.72  112.73  112.63  112.79
   113.5   113.8   115.3   115.5   114.5   116.1     116   115.2   114.9   115.2
     115   115.4   117.9   118.6   118.3   118.6     119   118.8
   119.6   119.3   118.3   118.3   118.7   119.2   117.6   116.7   115.1   114.8
   115.5   113.2   113.8   115.1   115.4   115.8   114.4  114.07  113.62  111.82
  111.36  111.36  111.27  110.58  112.25  112.36  112.28  111.93  111.73  111.69
   113.5   113.8   115.3   115.5   114.5   116.1     116   115.2   114.9   115.2
     115   115.4   117.9   118.6   118.3   118.6     119   118.8
  4037.3  4197.3  4217.3  4247.3  4317.3  4347.3  4387.3  4447.3  4497.3  4527.3
  4567.3  4647.3  4677.3  4697.3  4733.2  4863.2    4909  4913.4  4928.3 4934.41
    4936  5065.7 5072.29  5072.4  5080.2  5093.4  5114.6  5211.3  5264.7  5275.4
  5323.9    5354    5384    5454    5494    5554    5584    5594    5604    5614
    5634    5644    5664    5674    5864    5974    6064  6069.8
   119.6   119.3   118.3   118.3   118.7   119.2   117.6   116.7   115.1   114.8
   115.5   113.2   113.8   115.1   115.4  115.81  114.41  114.08  113.63  113.36
  113.36  113.36  113.27  113.27  113.17     113  112.72  112.73  112.63  112.79
   113.5   113.8   115.3   115.5   114.5   116.1     116   115.2   114.9   115.2
     115   115.4   117.9   118.6   118.3   118.6     119   118.8
   119.6   119.3   118.3   118.3   118.7   119.2   117.6   116.7   115.1   114.8
   115.5   113.2   113.8   115.1   115.4   115.8   114.4  114.07  113.62  111.82
  111.36  111.36  111.27  110.58  112.25  112.36  112.28  111.93  111.73  111.69
   113.5   113.8   115.3   115.5   114.5   116.1     116   115.2   114.9   115.2
     115   115.4   117.9   118.6   118.3   118.6     119   118.8
Pier Skew, UpSta & Num, DnSta & Num=  ,4977.6, 2 ,4977.6, 2 , 0 , 0 , 0 ,,
     1.4     1.4
   99.26  112.36
     1.4     1.4
   99.26  112.36
Pier Skew, UpSta & Num, DnSta & Num=  ,5022.4, 2 ,5022.4, 2 , 0 , 0 , 0 ,,
     1.4     1.4
   98.74  112.36
     1.4     1.4
   98.74  112.36
Abutment Skew #Up #Dn= , 2 , 2
  5065.4 5072.49
  109.09  111.27
  5065.4 5072.49
  109.09  111.27
BR Coef= 1 , 1 , 1 ,1.25, 0 ,,,.8,0,2,0,
WSPro=,,,, 1 ,,,, 0 ,,,, 0 ,,,,-1 ,-1 ,-1 , 0 , 0 , 0 , 0 , 0
BR U #Sta/Elev= 67
  4037.3   119.6  4197.3   119.3  4217.3   118.3  4247.3   118.3  4317.3   118.7
  4347.3   119.2  4387.3   117.6  4447.3   116.7  4497.3   115.1  4527.3   114.8
  4567.3   115.5  4647.3   113.2  4677.3   113.8  4697.3   115.1  4733.2   115.4
    4755  115.47  4757.1  115.47  4800.1  115.61  4840.9  115.73  4863.2   115.8
  4887.9  115.04    4909   114.4  4913.4  114.07  4928.3  113.62 4934.41  111.82
  4934.5  111.79  4934.6  111.76  4935.1  111.62    4936  111.35  4972.6  101.41
  4975.5  100.53  4985.6   99.54    4986   97.78    4995   94.18  5001.2   92.89
  5004.9   94.11  5012.1   97.69  5027.4  100.98  5065.4  109.09  5065.7  109.15
 5072.29  110.56  5072.4  110.58  5080.2  112.25  5093.4  112.36  5114.6  112.28
  5211.3  111.93  5264.7  111.73  5275.4  111.69  5323.9   113.5    5324   113.5
    5354   113.8    5384   115.3    5454   115.5    5494   114.5    5554   116.1
    5584     116    5594   115.2    5604   114.9    5614   115.2    5634     115
    5644   115.4    5664   117.9    5674   118.6    5864   118.3    5974   118.6
    6064     119  6069.8   118.8
BR U #Mann= 7
  4037.3      .1    4909    .045  4928.3    .015  4972.6     .04  5027.4    .015
  5080.2    .045  5093.4      .1
BR U Banks=4928.3,5080.2
BR D #Sta/Elev= 67
  4037.3   119.6  4197.3   119.3  4217.3   118.3  4247.3   118.3  4317.3   118.7
  4347.3   119.2  4387.3   117.6  4447.3   116.7  4497.3   115.1  4527.3   114.8
  4567.3   115.5  4647.3   113.2  4677.3   113.8  4697.3   115.1  4733.2   115.4
    4755  115.47  4757.1  115.47  4800.1  115.61  4840.9  115.73  4863.2   115.8
  4887.9  115.04    4909   114.4  4913.4  114.07  4928.3  113.62 4934.41  111.82
  4934.5  111.79  4934.6  111.76  4935.1  111.62    4936  111.35  4972.6  101.41
  4975.5  100.53  4985.6   99.54    4986   97.78    4995   94.18  5001.2   92.89
  5004.9   94.11  5012.1   97.69  5027.4  100.98  5065.4  109.09  5065.7  109.15
 5072.29  110.56  5072.4  110.58  5080.2  112.25  5093.4  112.36  5114.6  112.28
  5211.3  111.93  5264.7  111.73  5275.4  111.69  5323.9   113.5    5324   113.5
    5354   113.8    5384   115.3    5454   115.5    5494   114.5    5554   116.1
    5584     116    5594   115.2    5604   114.9    5614   115.2    5634     115
    5644   115.4    5664   117.9    5674   118.6    5864   118.3    5974   118.6
    6064     119  6069.8   118.8
BR D #Mann= 7
  4037.3      .1    4909    .045  4928.3    .015  4972.6     .04  5027.4    .015
  5080.2    .045  5093.4      .1
BR D Banks=4928.3,5080.2
BC Design=,, 0 ,, 0 ,,,,,,

Type RM Length L Ch R = 1 ,2579.1  ,116.8,100.1,85.7
BEGIN DESCRIPTION:
Downstream Section of Bridge/Culvert/Weir
END DESCRIPTION:
XS GIS Cut Line= 5
      3066054.19     13931309.11      3065522.28     13929203.58
      3065552.08     13929033.73      3065565.77     13928855.05
      3065327.64     13927895.13
#Sta/Elev= 30
  2551.7  124.37  2671.7  125.76  2911.7  125.08  2991.7  122.58  3051.7  125.05
  3121.7  124.89  3251.7  121.89  3511.7  123.35  3651.7  122.36  3701.7  120.24
  3891.7  120.53  4031.7  117.48  4037.3  119.59  4347.3  119.19  4647.3  113.19
  4733.2  115.39    4909  114.39  4928.3  113.61  4975.5  100.52  4985.6   99.53
    4986   97.77  5001.2   92.88  5012.1   97.68  5080.2  112.24  5093.4  112.35
  5275.4  111.68    5384  115.29    5634  114.99    5674  118.59  6069.8  118.79
#Mann= 5 ,-1 , 0
  2551.7      .1       0    4909    .045       0  4928.3     .04       0
  5080.2    .045       0  5093.4      .1       0
#XS Ineff= 2 , 0
       0  4918.3   113.2  5090.2       0  112.63
Permanent Ineff=
       F       F
Bank Sta=4928.3,5080.2
XS Rating Curve= 0
Exp/Cntr=.5,.3

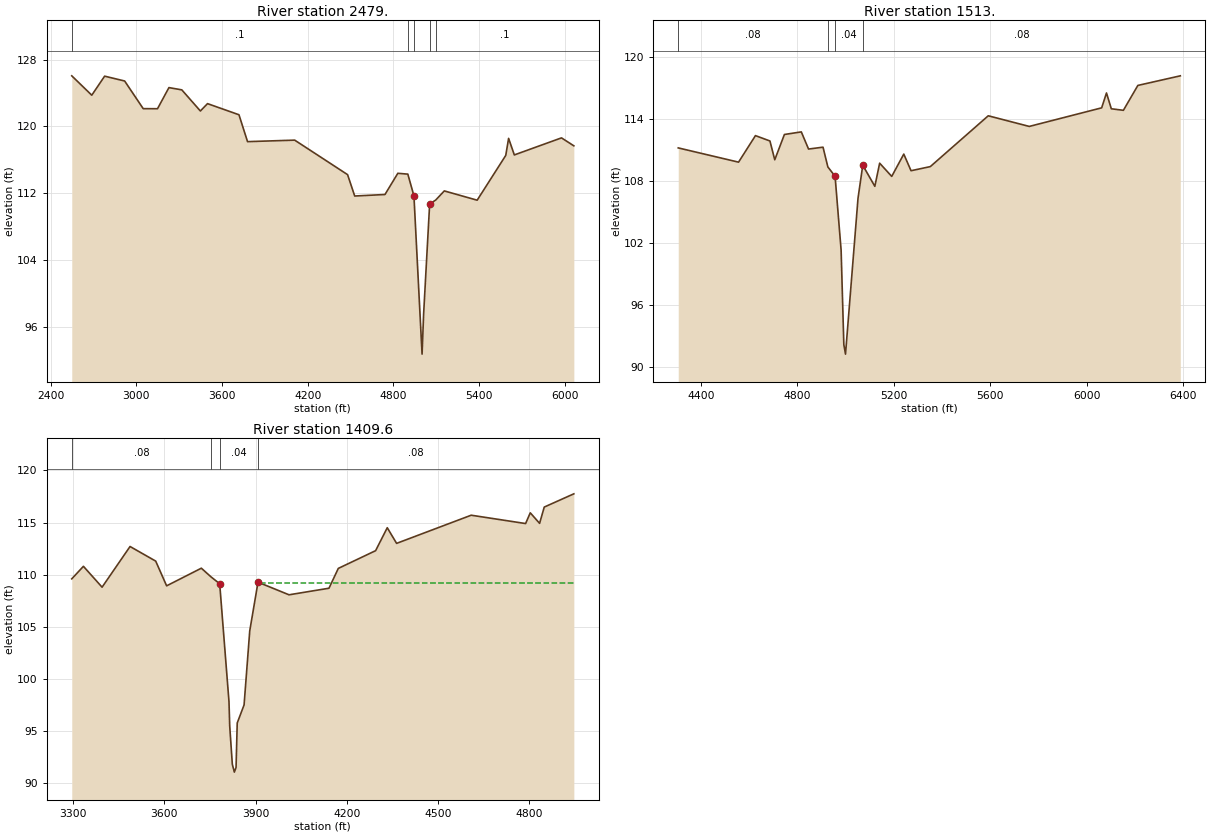
Type RM Length L Ch R = 1 ,2479.   ,967.3,965.98,965.1
BEGIN DESCRIPTION:
K133-00-00-S2_CHAMPION FOREST DR-DS - XS 1
END DESCRIPTION:
XS GIS Cut Line= 5
      3066151.64      13931284.7      3065619.74     13929179.22
      3065670.74     13928962.37      3065644.56     13928852.96
       3065425.1     13927870.77
#Sta/Elev= 30
  2548.7  126.05  2688.7  123.73  2778.7  126.01  2918.7  125.43  3048.7  122.12
  3148.7  122.11  3228.7  124.64  3318.7  124.37  3448.7  121.84  3498.7  122.72
  3718.7  121.39  3778.7  118.17  4108.7  118.35  4478.7  114.22  4528.7  111.66
  4740.4  111.84  4830.4  114.38  4900.4  114.28  4943.1  111.68    5000   92.73
 5010.88   97.53  5053.1  110.71    5095  111.17  5155.6  112.27  5385.6  111.16
  5585.6  116.52  5605.6  118.56  5645.6  116.58  5975.6  118.62  6062.1  117.67
#Mann= 5 ,-1 , 0
  2548.7      .1       0  4900.4    .045       0  4943.1     .04       0
  5053.1    .045       0    5095      .1       0
Bank Sta=4943.1,5053.1
XS Rating Curve= 0
Exp/Cntr=.3,.1

Type RM Length L Ch R = 1 ,1513.   ,134.1,103.4,52.9
BEGIN DESCRIPTION:
K133-00-00-S1_CYPRESSWOOD DR-US - XS 4
END DESCRIPTION:
XS GIS Cut Line= 4
      3067069.09      13929236.9      3066616.12     13928763.86
      3066589.49     13928657.34      3065477.46     13927953.91
#Sta/Elev= 30
  4306.8  111.21  4556.8  109.83  4626.8   112.4  4686.8  111.88  4706.8  110.06
  4746.8  112.51  4816.8  112.76  4846.8   111.1  4906.8  111.28  4926.8  109.37
  4956.8  108.46  4981.8   101.3 4993.04   92.17    5000   91.24  5051.8  106.33
  5071.5  109.53  5121.5  107.49  5141.5  109.73  5191.5  108.45  5241.5  110.61
  5271.5     109  5351.5   109.4  5591.5  114.32  5761.5  113.29  6061.5  115.09
  6081.5  116.53  6101.5     115  6151.5  114.85  6211.5  117.26  6387.4  118.19
#Mann= 4 ,-1 , 0
  4306.8     .08       0  4926.8    .045       0  4956.8     .04       0
  5071.5     .08       0
Bank Sta=4956.8,5071.5
XS Rating Curve= 0
Exp/Cntr=.5,.3

Type RM Length L Ch R = 1 ,1409.6  ,120,121.5,138.4
BEGIN DESCRIPTION:
Upstream Section of Bridge/Culvert/Weir
END DESCRIPTION:
XS GIS Cut Line= 4
      3067168.76     13929216.97      3066936.07     13928875.86
      3066501.72     13928554.33      3065508.56      13927891.2
#Sta/Elev= 30
 3296.06  109.613334.362  110.813395.645  108.813487.571  112.713571.835  111.31
3607.763  108.943721.827  110.633753.924  109.793782.115  109.14 3812.68   97.83
3815.055    95.53823.634   91.833830.299   91.083835.891   91.533839.721   95.79
3862.243   97.523880.858  104.623908.052  109.294009.936  108.084141.236  108.71
4171.878  110.614294.445  112.314332.748  114.514363.389  113.014608.523  115.71
4787.318  114.914802.639  115.944833.281  114.934848.602  116.494945.812  117.76
#Mann= 4 ,-1 , 0
 3296.06     .08       03753.924    .045       03782.115     .04       0
3908.052     .08       0
#XS Ineff= 2 , 0
       03774.454   108.83915.713       0  109.25
Permanent Ineff=
       F       F
Bank Sta=3782.115,3908.052
XS Rating Curve= 0
Skew Angle= 40
Exp/Cntr=.5,.3