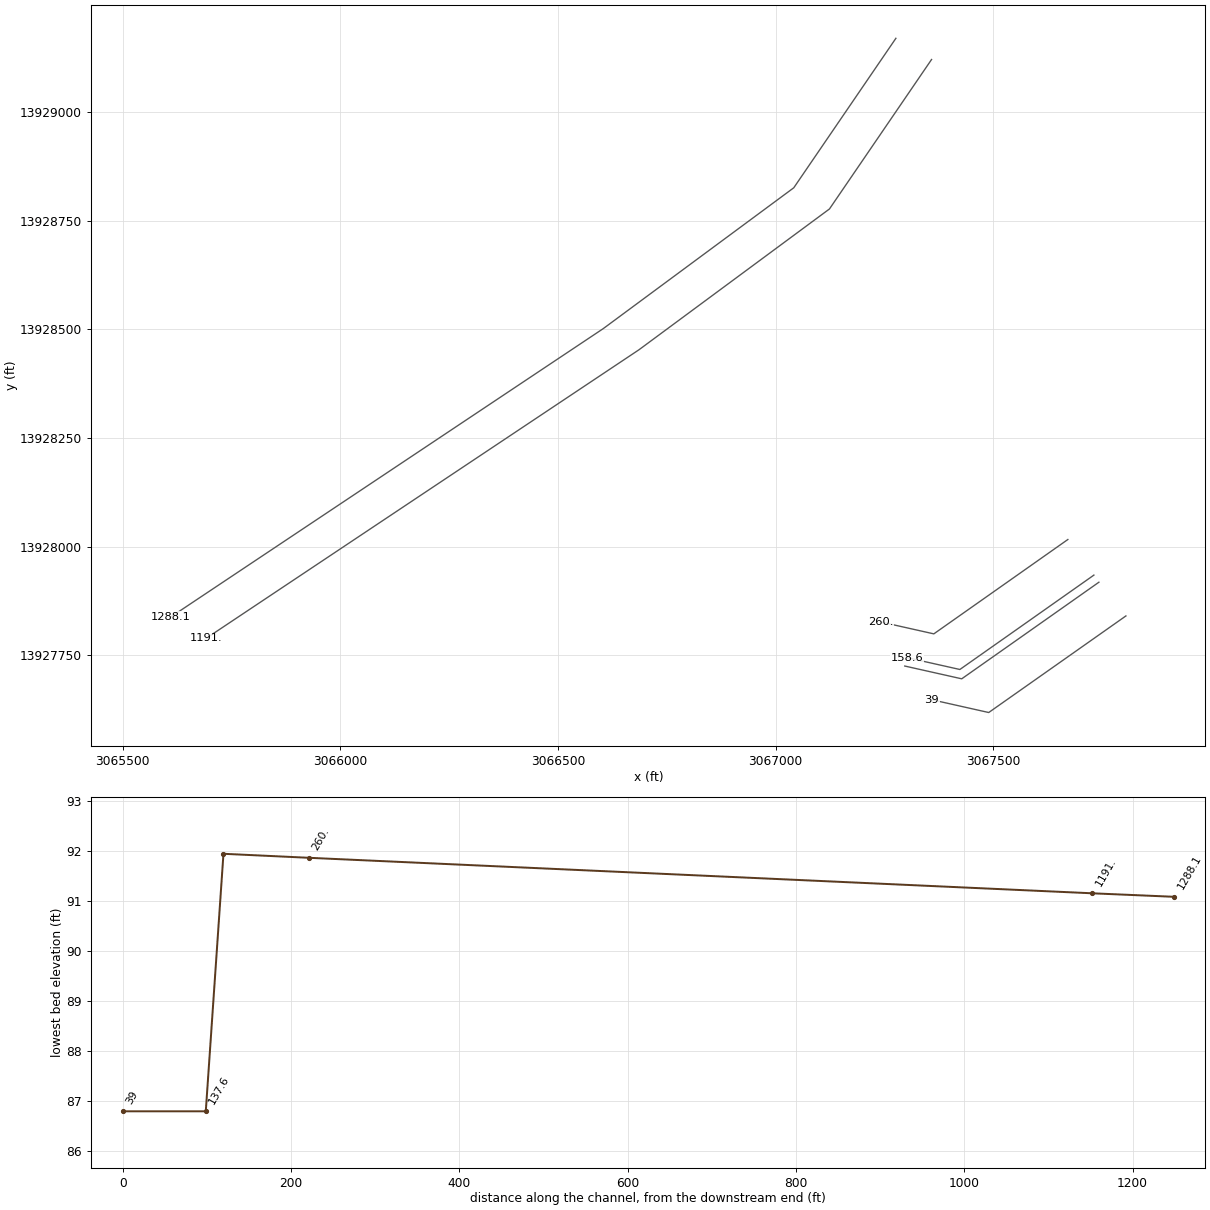
HEC-RAS study K133-00-00.prj: K133-00-00

--- K133-00-00.g01 (geometry) --- (continued)

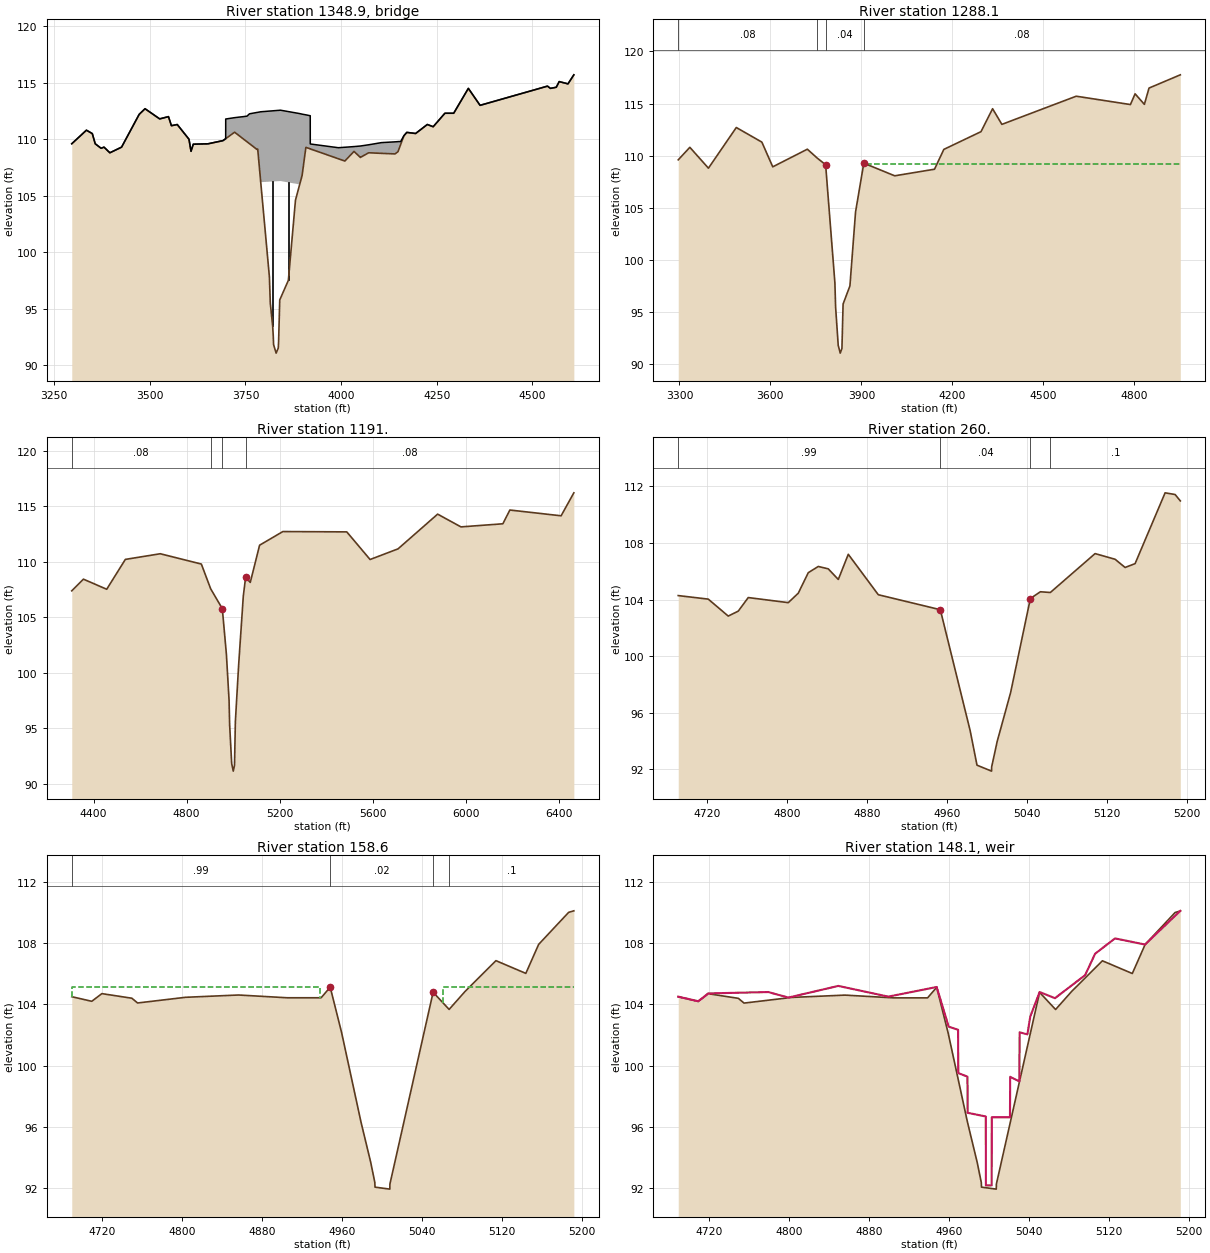
Type RM Length L Ch R = 3 ,1348.9  ,,,
BEGIN DESCRIPTION:
CYPRESSWOOD DR
Structure ID: K133-00-00-S1
END DESCRIPTION:
Bridge Culvert--1,0,-1,-1, 0
Deck Dist Width WeirC Skew NumUp NumDn MinLoCord MaxHiCord MaxSubmerge Is_Ogee
10,108,2.6,40, 57, 57, , , .95, 0, 1,1,,
 3296.063334.3623349.6833357.3433372.6643380.3243395.6453426.287 3472.253487.571
3525.8733548.8543556.5153571.8353602.4773607.7633613.738 3652.273691.2623698.378
3698.4633721.8273753.9243760.5893779.9693782.115 3790.023841.7133891.8663898.247
3908.0523919.4663919.5513993.0074009.9364033.8374050.5374072.2924105.6154141.236
4148.8964155.8684164.2184171.8784194.8594225.5014240.8224271.4644294.4454332.748
4363.3894539.579 4547.244562.5614570.2214593.2034608.523
   109.6   110.8   110.5   109.6   109.2   109.3   108.8   109.3   112.2   112.7
   111.8     112   111.2   111.3     110  108.93  109.56   109.6  109.88  110.05
  111.79  111.91  112.04  112.25  112.37  112.38  112.43  112.57  112.27  112.22
  112.16  112.08  109.58  109.25  109.29  109.35   109.4  109.51   109.7  109.77
  109.79   109.8  110.31  110.61  110.51  111.31  111.11   112.3   112.3   114.5
     113   114.7   114.5   114.6   115.1   114.9   115.7
   109.6   110.8   110.5   109.6   109.2   109.3   108.8   109.3   112.2   112.7
   111.8     112   111.2   111.3     110  108.93  109.56  109.59  109.87  110.04
  110.05  110.62  109.78  109.61   109.1  109.13   106.2   106.3     106   106.8
  109.28  109.14  109.14  108.27  108.07  108.92  108.39   108.8  108.75   108.7
   108.9  109.54   110.3   110.6   110.5   111.3   111.1   112.3   112.3   114.5
     113   114.7   114.5   114.6   115.1   114.9   115.7
 3296.063334.3623349.6833357.3433372.6643380.3243395.6453426.287 3472.253487.571
3525.8733548.8543556.5153571.8353602.4773607.7633613.738 3652.273691.2623698.378
3698.4633721.8273753.9243760.5893779.9693782.115 3790.023841.7133891.8663898.247
3908.0523919.4663919.5513993.0074009.9364033.8374050.5374072.2924105.6154141.236
4148.8964155.8684164.2184171.8784194.8594225.5014240.8224271.4644294.4454332.748
4363.3894539.579 4547.244562.5614570.2214593.2034608.523
   109.6   110.8   110.5   109.6   109.2   109.3   108.8   109.3   112.2   112.7
   111.8     112   111.2   111.3     110  108.93  109.56   109.6  109.88  110.05
  111.79  111.91  112.04  112.25  112.37  112.38  112.43  112.57  112.27  112.22
  112.16  112.08  109.58  109.25  109.29  109.35   109.4  109.51   109.7  109.77
  109.79   109.8  110.31  110.61  110.51  111.31  111.11   112.3   112.3   114.5
     113   114.7   114.5   114.6   115.1   114.9   115.7
   109.6   110.8   110.5   109.6   109.2   109.3   108.8   109.3   112.2   112.7
   111.8     112   111.2   111.3     110  108.93  109.56  109.59  109.87  110.04
  110.05  110.62  109.78  109.61   109.1  109.13   106.2   106.3     106   106.8
  109.28  109.14  109.14  108.27  108.07  108.92  108.39   108.8  108.75   108.7
   108.9  109.54   110.3   110.6   110.5   111.3   111.1   112.3   112.3   114.5
     113   114.7   114.5   114.6   115.1   114.9   115.7
Pier Skew, UpSta & Num, DnSta & Num=  ,3821.183, 2 ,3821.183, 2 , 0 , 0 , 0 ,,
     1.4     1.4
   92.18  107.26
     1.4     1.4
   92.18  107.26
Pier Skew, UpSta & Num, DnSta & Num=  ,3862.243, 2 ,3862.243, 2 , 0 , 0 , 0 ,,
     1.4     1.4
   96.47   107.2
     1.4     1.4
   96.47   107.2
BR Coef= 1 , 1 , 1 ,1.25, 0 ,,,.8,0,2,0,
WSPro=,,,, 1 ,,,, 0 ,,,, 0 ,,,,-1 ,-1 ,-1 , 0 , 0 , 0 , 0 , 0
BR U #Sta/Elev= 89
 3296.06   109.63334.362   110.83349.683   110.53357.343   109.63372.664   109.2
3380.324   109.33395.645   108.83426.287   109.3 3472.25   112.23487.571   112.7
3525.873   111.83548.854     1123556.515   111.23571.835   111.33602.477     110
3607.763  108.933613.738  109.563638.328  109.583647.137  109.59 3652.27  109.59
3685.823  109.833691.262  109.873698.378  110.043698.463  110.053698.547  110.05
3717.614  110.523721.827  110.623730.253   110.43753.924  109.783760.589  109.61
3779.969   109.13782.115  109.133789.951  106.23 3790.02   106.23801.419  101.99
 3812.68   97.823815.055   95.493821.183   93.473822.638   92.683823.634   91.82
3830.299   91.073835.891   91.52 3836.81   92.163839.721   95.783841.713   95.93
3862.243   97.51 3877.87  103.473880.858  104.613882.926  104.873891.781  105.99
3891.866     1063898.247   106.83908.052  109.283919.382  109.153919.466  109.14
3919.551  109.143957.002   108.73966.042  108.593993.007  108.274009.936  108.07
4033.837  108.924050.537  108.394051.992  108.424072.292   108.84105.615  108.75
4141.236   108.74148.896   108.94155.868  109.544164.218   110.34171.188  110.57
4171.878   110.6 4186.51  110.544194.859   110.54217.151  111.084225.501   111.3
4232.472  111.214240.822   111.14252.083  111.544271.464   112.34294.445   112.3
4332.748   114.54363.389     1134507.865  114.394539.579   114.7 4547.24   114.5
4562.561   114.64570.221   115.14593.203   114.94608.523   115.7
BR U #Mann= 4
 3296.06     .083753.924    .0453782.115     .043908.052     .08
BR U Banks=3782.115,3908.052
BR D #Sta/Elev= 89
 3296.06   109.63334.362   110.83349.683   110.53357.343   109.63372.664   109.2
3380.324   109.33395.645   108.83426.287   109.3 3472.25   112.23487.571   112.7
3525.873   111.83548.854     1123556.515   111.23571.835   111.33602.477     110
3607.763  108.933613.738  109.563638.328  109.583647.137  109.59 3652.27  109.59
3685.823  109.833691.262  109.873698.378  110.043698.463  110.053698.547  110.05
3717.614  110.523721.827  110.623730.253   110.43753.924  109.783760.589  109.61
3779.969   109.13782.115  109.133789.951  106.23 3790.02   106.23801.419  101.99
 3812.68   97.823815.055   95.493821.183   93.473822.638   92.683823.634   91.82
3830.299   91.073835.891   91.52 3836.81   92.163839.721   95.783841.713   95.93
3862.243   97.51 3877.87  103.473880.858  104.613882.926  104.873891.781  105.99
3891.866     1063898.247   106.83908.052  109.283919.382  109.153919.466  109.14
3919.551  109.143957.002   108.73966.042  108.593993.007  108.274009.936  108.07
4033.837  108.924050.537  108.394051.992  108.424072.292   108.84105.615  108.75
4141.236   108.74148.896   108.94155.868  109.544164.218   110.34171.188  110.57
4171.878   110.6 4186.51  110.544194.859   110.54217.151  111.084225.501   111.3
4232.472  111.214240.822   111.14252.083  111.544271.464   112.34294.445   112.3
4332.748   114.54363.389     1134507.865  114.394539.579   114.7 4547.24   114.5
4562.561   114.64570.221   115.14593.203   114.94608.523   115.7
BR D #Mann= 4
 3296.06     .083753.924    .0453782.115     .043908.052     .08
BR D Banks=3782.115,3908.052
BC Design=,, 0 ,, 0 ,,,,,,

Type RM Length L Ch R = 1 ,1288.1  ,94.6,97.1,104.4
BEGIN DESCRIPTION:
Downstream Section of Bridge/Culvert/Weir
END DESCRIPTION:
XS GIS Cut Line= 4
      3067276.29     13929169.39      3067041.69     13928825.49
      3066604.24     13928501.66      3065610.67     13927838.26
#Sta/Elev= 30
 3296.06  109.613334.362  110.813395.645  108.813487.571  112.713571.835  111.31
3607.763  108.943721.827  110.633753.924  109.793782.115  109.14 3812.68   97.83
3815.055    95.53823.634   91.833830.299   91.083835.891   91.533839.721   95.79
3862.243   97.523880.858  104.623908.052  109.294009.936  108.084141.236  108.71
4171.878  110.614294.445  112.314332.748  114.514363.389  113.014608.523  115.71
4787.318  114.914802.639  115.944833.281  114.934848.602  116.494951.788  117.76
#Mann= 4 ,-1 , 0
 3296.06     .08       03753.924    .045       03782.115     .04       0
3908.052     .08       0
#XS Ineff= 2 , 0
       03774.454   108.83915.713       0  109.25
Permanent Ineff=
       F       F
Bank Sta=3782.115,3908.052
XS Rating Curve= 0
Skew Angle= 40
Exp/Cntr=.5,.3

Type RM Length L Ch R = 1 ,1191.   ,930,931,930.1
BEGIN DESCRIPTION:
K133-00-00-S1_CYPRESSWOOD DR-DS - XS 1
END DESCRIPTION:
XS GIS Cut Line= 4
       3067358.2      13929120.6      3067123.65     13928776.76
      3066686.19     13928452.93      3065692.62     13927789.53
#Sta/Elev= 30
  4306.7   107.4  4356.7  108.45  4456.7  107.54  4536.7  110.23  4686.7  110.74
    4863  109.81    4903  107.58    4953  105.79 4970.47  101.69 4981.96   97.54
 4984.39   95.34 4993.14   91.84 4999.94   91.15 5005.32   91.67    5009   95.61
    5023  100.69    5043   106.9    5053  108.62    5073  108.16    5113  111.51
    5213  112.74  5487.3  112.71  5587.3  110.22  5707.3  111.18  5877.3  114.31
  5977.3  113.16  6157.3  113.44  6187.3  114.68  6407.3  114.16    6462  116.23
#Mann= 4 ,-1 , 0
  4306.7     .08       0    4903    .045       0    4953     .04       0
    5053     .08       0
Bank Sta=4953,5053
XS Rating Curve= 0
Exp/Cntr=.3,.1

Type RM Length L Ch R = 1 ,260.    ,100,101.4,101.5
BEGIN DESCRIPTION:
K133-00-00-S01_WEIR - US - XS 4
END DESCRIPTION:
XS GIS Cut Line= 4
       3067671.3      13928016.4       3067481.7      13927882.7
      3067363.43     13927799.35      3067241.26      13927826.8
#Sta/Elev= 30
  4691.2  104.28  4721.2  104.03  4741.2  102.83  4751.2  103.18  4761.2  104.14
  4801.2  103.78  4811.2  104.45  4821.2   105.9  4831.2  106.34  4841.2  106.17
  4851.2  105.42  4861.2   107.2  4891.2  104.34  4953.2  103.28    4983   94.73
 4989.87   92.28 5004.42   91.86 5004.52   92.16 5010.04   93.96 5023.48   97.42
  5043.2  104.07  5053.2  104.55  5063.2   104.5  5107.9  107.25  5127.9  106.85
  5137.9  106.27  5147.9  106.54  5177.9  111.55  5187.9  111.43  5193.1  110.98
#Mann= 4 ,-1 , 0
  4691.2     .99       0  4953.2     .04       0  5043.2    .045       0
  5063.2      .1       0
Bank Sta=4953.2,5043.2
XS Rating Curve= 0
Exp/Cntr=.7,.5

Type RM Length L Ch R = 1 ,158.6   ,19,21,20
BEGIN DESCRIPTION:
Upstream Section of Bridge/Culvert/Weir
END DESCRIPTION:
XS GIS Cut Line= 4
      3067731.11     13927934.52       3067541.5     13927800.74
      3067423.23      13927717.4      3067301.06     13927744.85
#Sta/Elev= 25
  4689.5  104.49  4709.5  104.19  4719.6  104.69  4749.6  104.39  4755.3  104.08
  4803.2  104.45  4856.2   104.6  4904.8  104.42  4938.8  104.42  4947.9  105.11
  4959.3  102.15  4978.7   96.31  4988.4   93.69  4992.5   92.38  4992.7   92.07
  5007.5   91.94  5007.6   92.27  5050.8  104.78  5066.8  103.66  5082.7  104.83
  5113.6  106.84  5143.5  106.01  5156.3   107.9  5186.3  109.99  5191.5  110.09
#Mann= 4 ,-1 , 0
  4689.5     .99       0  4947.9     .02       0  5050.8    .045       0
  5066.8      .1       0
#XS Ineff= 2 , 0
       0  4937.9   105.1  5060.8       0   105.1
Permanent Ineff=
       F       F
Bank Sta=4947.9,5050.8
XS Rating Curve= 0
Exp/Cntr=.7,.5

Type RM Length L Ch R = 5 ,148.1   ,,,
BEGIN DESCRIPTION:
1200' DS CYPRESSWOOD
Structure ID: K133-00-00-S01
END DESCRIPTION:
IW Pilot Flow=0
#Inline Weir SE= 30
  4689.5   104.5  4709.5   104.2  4719.5  104.71  4779.5   104.8  4799.6  104.44
  4849.6   105.2  4899.5   104.5  4947.9  105.13  4959.9  102.54  4969.3  102.34
  4969.5   99.51  4978.7   99.28  4978.8   96.92    4997   96.68  4997.1   92.18
  5002.9   92.18    5003   96.63  5021.2   96.63  5021.4   99.27  5030.6   98.97
  5030.8  102.17  5038.6  102.04  5041.5   103.2  5050.8   104.8  5066.2   104.4
  5096.3   105.9  5106.3   107.3  5126.2   108.3  5156.2   107.9  5191.5   110.1
IW Dist,WD,Coef,Skew,MaxSub,Min_El,Is_Ogee,SpillHt,DesHd
10,1,3,0,.95,, 0 ,,,0,0,

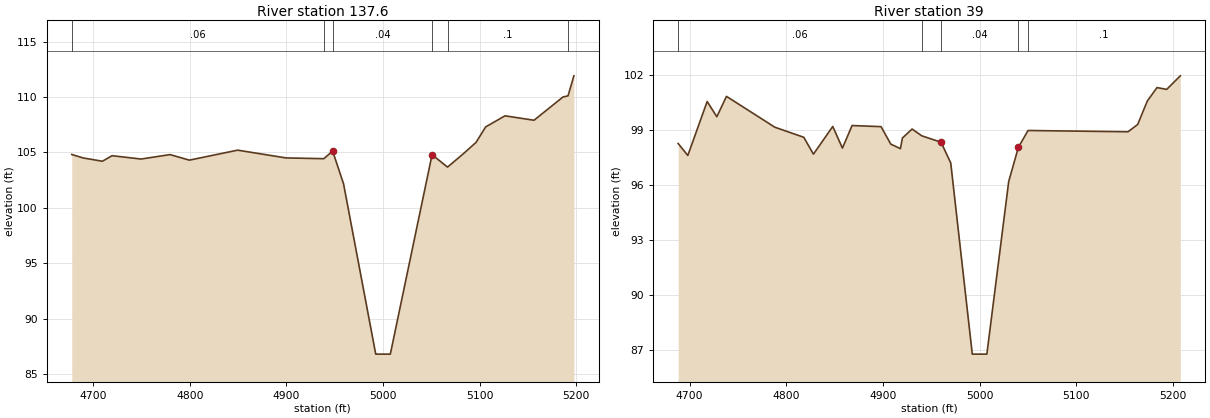
Type RM Length L Ch R = 1 ,137.6   ,98,98.6,99
BEGIN DESCRIPTION:
Cross Section FIELD_DS
Located At: 1200' DS CYPRESSWOOD
END DESCRIPTION:
XS GIS Cut Line= 4
      3067742.63     13927918.17      3067553.02      13927784.4
       3067427.5     13927695.94      3067296.68     13927725.34
#Sta/Elev= 24
  4677.9  104.81  4689.6   104.5  4709.6   104.2  4719.6   104.7  4749.6   104.4
  4779.6   104.8  4799.6   104.3  4849.6   105.2  4899.6   104.5  4938.8  104.43
  4947.9  105.12  4959.2  102.16  4992.5   86.79  5007.6   86.79  5050.8  104.79
  5066.8  103.67  5082.7  104.84  5096.3   105.9  5106.3   107.3  5126.3   108.3
  5156.3   107.9  5186.3     110  5191.5   110.1  5197.6  111.91
#Mann= 6 ,-1 , 0
  4677.9     .06       0  4938.8    .045       0  4947.9     .04       0
  5050.8    .045       0  5066.8      .1       0  5191.5     .99       0
Bank Sta=4947.9,5050.8
XS Rating Curve= 0
Exp/Cntr=.7,.5

Type RM Length L Ch R = 1 ,39      ,0,0,0
BEGIN DESCRIPTION:
Cross Section FIELD_DSK133-00-00-S01_WEIR - DS - XS 1
Located At: 1200' DS CYPRESSWOOD
END DESCRIPTION:
XS GIS Cut Line= 4
      3067804.65      13927840.6      3067615.04     13927706.88
      3067489.52     13927618.42       3067358.7     13927647.81
#Sta/Elev= 30
  4688.1   98.27  4698.1   97.62  4718.1  100.56  4728.1   99.73  4738.1  100.84
  4788.1   99.16  4818.1   98.61  4828.1   97.69  4848.1    99.2  4858.1   98.02
  4868.1   99.25  4898.1   99.19  4908.1   98.24  4918.1   97.99  4920.2   98.57
  4930.2   99.06  4940.2   98.69  4960.2   98.34  4970.2   97.21  4992.5   86.79
  5007.6   86.79  5030.2    96.2  5040.2   98.06  5050.2   98.98  5153.7   98.91
  5163.7   99.31  5173.7  100.59  5183.7  101.32  5193.7  101.22  5207.8  101.96
#Mann= 5 ,-1 , 0
  4688.1     .06       0  4940.2    .045       0  4960.2     .04       0
  5040.2    .045       0  5050.2      .1       0
Bank Sta=4960.2,5040.2
XS Rating Curve= 0
Exp/Cntr=.3,.1

Chan Stop Cuts=-1